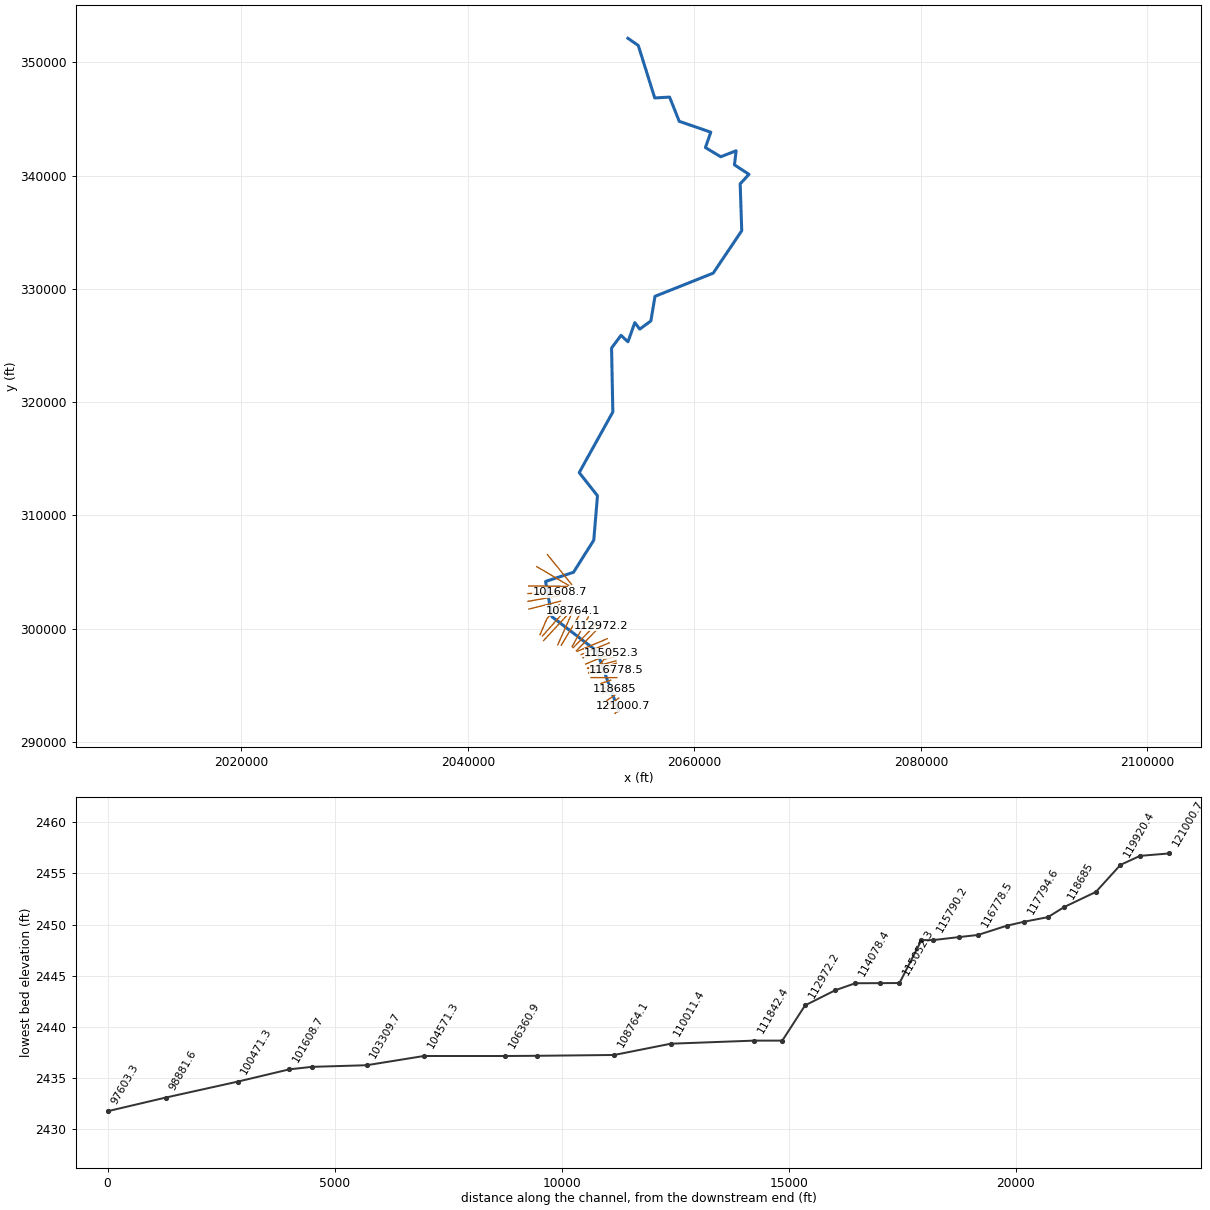
--- MeadowRv2.prj (project) ---

Proj Title=MeadowRv2
Current Plan=p01
Default Exp/Contr=0,0
English Units
Geom File=g01
Flow File=f01
Plan File=p01
BEGIN DESCRIPTION:
END DESCRIPTION:
DSS Export Rating Curves= 0
DSS Export Rating Curve Sorted= 0
DSS Export Volume Flow Curves= 0
DXF OffsetX= 0
DXF OffsetY= 0
DXF ScaleX= 0
DXF ScaleY= 0

--- MeadowRv2.p01 (plan) ---

Plan Title=Floodplain
Program Version=4.00
Geom File=g01
Flow File=f01
K Sum by GR=0
Std Step Tol=0.01
Critical Tol=0.01
Num of Std Step Trials=20
Max Error Tol=0.3
Flow Tol Ratio=0.001
Split Flow NTrial=30
Split Flow Tol=0.02
Split Flow Ratio=0.02
Log Output Level=0
Friction Slope Method=1
Unsteady Friction Slope Method=2
Unsteady Bridges Friction Slope Method=1
Global Log Level=0
CheckData=False
Run HTab=0
Run UNet=0
Run PostProcess=0
UNET Theta=0
UNET Theta Warmup=0
UNET ZTol=0
UNET ZSATol=0
UNET MxIter=0
UNET MaxInSteps=0
UNET DtIC=0
UNET DtMin=0
UNET MaxCRTS=0
UNET WFStab=0
UNET SFStab=0
UNET WFX=0
UNET SFX=0
UNET DSS MLevel=0
UNET DZMax Abort=0
UNET Convert EG Bridges=0
UNET Use Existing IB Tables=0
UNET Froude Limit=0
UNET Froude Power=0
Write IC File=0
Echo Input=False
Echo Output=False
Write Detailed=0

--- MeadowRv2.f01 (steady flow) ---

Flow Title=NFF Regression Equation
Program Version=4.00
Number of Profiles=1
Profile Names=P100yr
River Rch & RM=MeadowRv2,Main      ,121000.7
586.3125
River Rch & RM=MeadowRv2,Main      ,115790.2
645.7131
River Rch & RM=MeadowRv2,Main      ,115052.3
860.4980
River Rch & RM=MeadowRv2,Main      ,113634.2
893.1257
River Rch & RM=MeadowRv2,Main      ,110011.4
987.5373
River Rch & RM=MeadowRv2,Main      ,107066.4
1057.313
River Rch & RM=MeadowRv2,Main      ,104571.3
1149.731
River Rch & RM=MeadowRv2,Main      ,103309.7
1696.387
River Rch & RM=MeadowRv2,Main      ,100471.3
1717.870
River Rch & RM=MeadowRv2,Main      ,98881.6
1905.360
River Rch & RM=MeadowRv2,Main      ,92684.8
2095.631
River Rch & RM=MeadowRv2,Main      ,83772.5
2315.858
River Rch & RM=MeadowRv2,Main      ,83232.5
2816.301
River Rch & RM=MeadowRv2,Main      ,82175.6
2852.800
River Rch & RM=MeadowRv2,Main      ,80345.5
3597.851
River Rch & RM=MeadowRv2,Main      ,69042
3787.652
River Rch & RM=MeadowRv2,Main      ,66097.1
4198.399
River Rch & RM=MeadowRv2,Main      ,59857.1
4302.235
River Rch & RM=MeadowRv2,Main      ,55792.6
4521.299
River Rch & RM=MeadowRv2,Main      ,51242.1
4886.956
River Rch & RM=MeadowRv2,Main      ,30559.2
5409.833
River Rch & RM=MeadowRv2,Main      ,29245.7
7156.891
River Rch & RM=MeadowRv2,Main      ,25132.6
7354.606
River Rch & RM=MeadowRv2,Main      ,24733.9
10701.54
River Rch & RM=MeadowRv2,Main      ,10636.3
10866.09
River Rch & RM=MeadowRv2,Main      ,6334.7
15621.75
River Rch & RM=MeadowRv2,Main      ,14.2
15879.73
Boundary for River Rch & Prof#=MeadowRv2,Main      ,1
Up Type=0
Dn Type=3
Dn Slope=0.000467

--- MeadowRv2.g01 (geometry) ---

Geom Title=USGS 10m DEM
Program Version=4.10

River Reach=MeadowRv2       ,Main
Reach XY= 30
     2053302.817      292766.881     2051386.765      298021.656
     2047425.129      301059.117     2046865.338      304171.362
     2049330.616      304978.653     2051120.546      307811.986
     2051449.084      311736.478     2049836.306      313780.052
     2052804.757      319134.065      2052692.72      324780.056
     2053526.878      325896.278     2054140.911      325327.918
     2054743.359      327022.971     2055180.045      326449.041
     2056162.142      327169.127     2056527.532       329341.86
     2061662.597      331388.044     2064184.678      335132.845
     2064047.055      339274.524     2064823.385      340111.059
     2063543.233      340953.931     2063690.585      342196.477
      2062331.49      341665.015     2060977.331      342477.839
     2061452.777      343833.508      2058665.74      344796.471
     2057816.781      346931.019     2056503.905      346858.261
      2055050.78      351490.206     2054141.146      352120.475

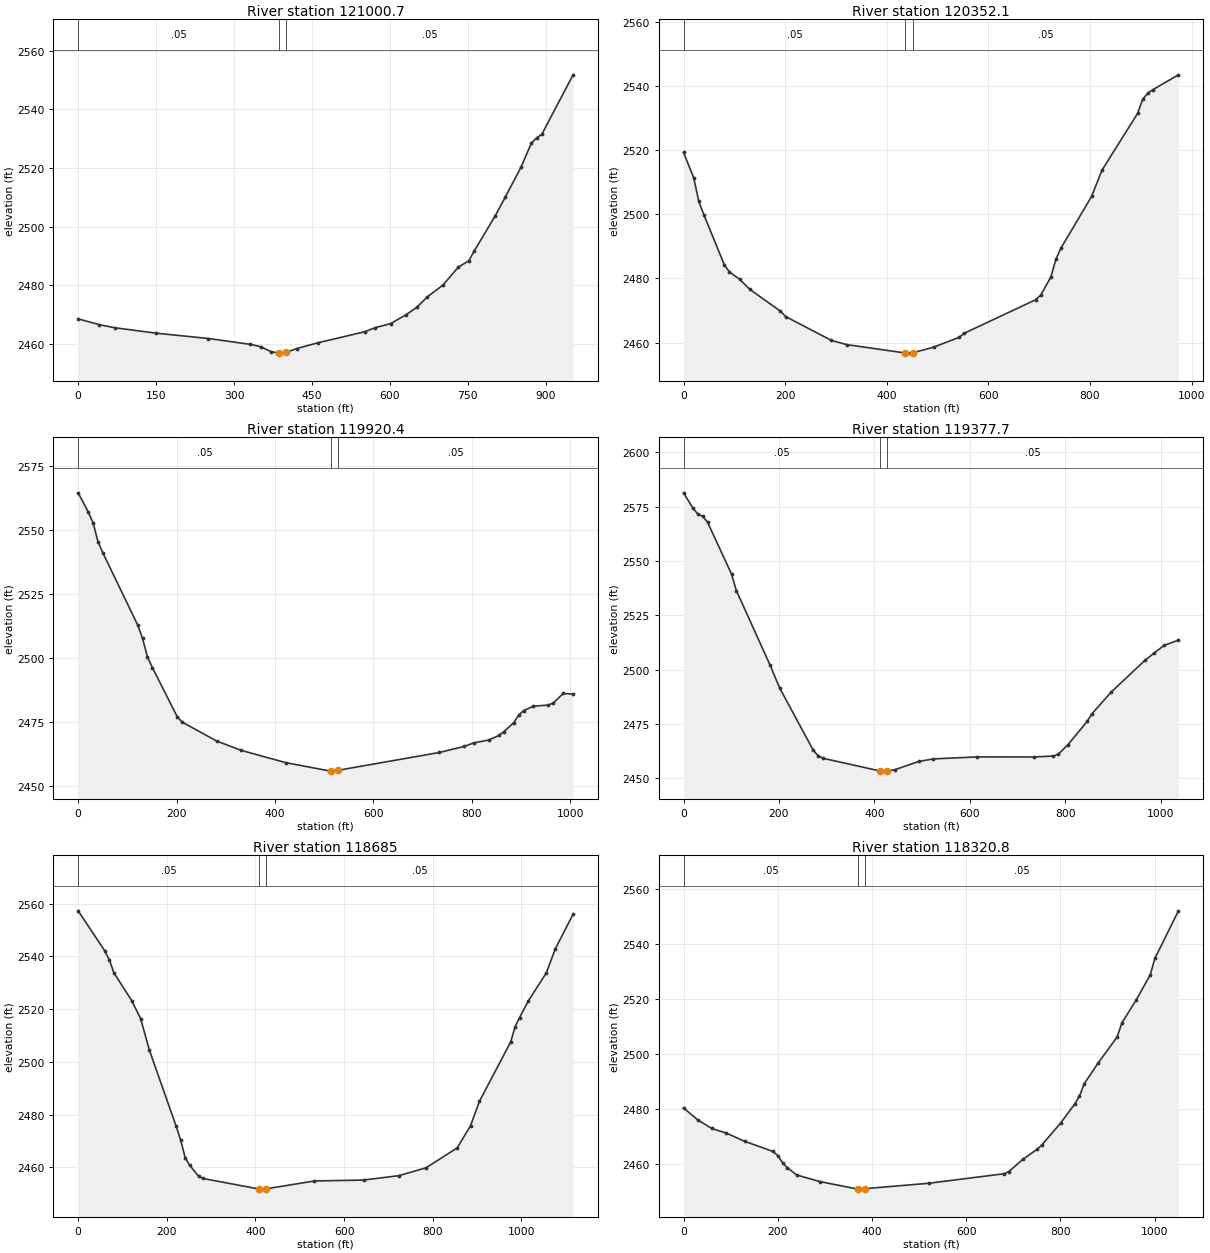
Type RM Length L Ch R = 1 ,121000.7,650,645.9,669.6
XS GIS Cut Line= 2
     2052996.252      292522.876     2053726.329      293134.736
#Sta/Elev= 30
       0 2468.61    40.1 2466.66    70.2 2465.59   150.4 2463.73   250.7 2461.92
   330.9 2459.94     351 2459.15     371 2457.47   385.6 2456.98     391 2456.94
   400.6 2457.24   421.1 2458.51   461.2 2460.45   551.5 2464.22   571.5  2465.6
   601.6    2467   631.7 2470.09   651.8 2472.54   671.8 2476.07   701.9 2480.08
     732  2486.3     752 2488.37     762 2491.64   802.2 2503.56   822.2 2510.11
   852.3 2520.26   872.4 2528.49   882.4 2530.24   892.4 2531.46   952.6 2551.73
#Mann= 3 , 0 , 0
       0     .05       0   385.6    .045       0   400.6     .05       0
Bank Sta=385.6,400.6
XS Rating Curve= 0 ,0
Exp/Cntr=0.3,0.1

Type RM Length L Ch R = 1 ,120352.1,467.5,432.1,438.6
XS GIS Cut Line= 2
     2052685.206      293022.694     2053551.039       293468.82
#Sta/Elev= 30
       0 2519.26    20.1 2511.35    30.1 2503.96    40.2 2499.77    80.3 2484.24
    90.4 2481.97   110.4 2479.73   130.5 2476.57   190.8 2469.78   200.8 2468.11
   291.2 2460.66   321.3 2459.35   436.2 2456.75   441.8  2456.7   451.2 2456.79
     492 2458.55   542.2  2461.6   552.3 2462.87   692.8 2473.32   702.9 2474.77
     723 2480.43     733 2486.02   743.1 2489.51   803.3 2505.58   823.4 2513.68
   893.7 2531.42   903.7 2535.82   913.8 2537.71   923.8 2538.82     974 2543.43
#Mann= 3 , 0 , 0
       0     .05       0   436.2    .045       0   451.2     .05       0
Bank Sta=436.2,451.2
XS Rating Curve= 0 ,0
Exp/Cntr=0.3,0.1

Type RM Length L Ch R = 1 ,119920.4,529.8,540.9,538.3
XS GIS Cut Line= 2
     2052506.507      293309.845     2053336.064      293878.537
#Sta/Elev= 30
       0 2564.54    20.1  2557.2    30.2 2552.91    40.2 2545.52    50.3 2541.06
   120.7 2513.01   130.8 2507.69   140.8 2500.45   150.9 2496.25   201.2 2477.11
   211.2 2474.99   281.6 2467.56   331.9  2463.9   422.4 2459.11   512.9 2455.82
   527.9 2456.14   734.2 2463.11   784.5 2465.48   804.6 2466.88   834.8 2467.99
   854.9 2469.74     865 2471.22   885.1 2474.72   895.1 2477.62   905.2 2479.48
   925.3 2481.17   955.5 2481.64   965.5 2482.42   985.7 2486.15  1005.8 2485.91
#Mann= 3 , 0 , 0
       0     .05       0   512.9    .045       0   527.9     .05       0
Bank Sta=512.9,527.9
XS Rating Curve= 0 ,0
Exp/Cntr=0.3,0.1

Type RM Length L Ch R = 1 ,119377.7,685.3,692,685.1
XS GIS Cut Line= 2
     2052285.587       293664.84     2053140.633      294251.006
#Sta/Elev= 30
       0  2581.4    20.1 2574.24    30.2 2571.58    40.3 2570.52    50.3 2567.88
   100.6 2543.96   110.7 2536.39   181.2 2502.09   201.3 2491.54   271.8 2462.79
   281.8 2460.29   291.9 2459.12   410.7 2453.29   422.7 2453.18   425.7 2453.24
   442.8 2453.84   493.2 2457.66   523.4  2458.8     614 2459.73   734.7  2459.7
     775 2460.14     785 2460.95   805.2 2465.33   845.4 2476.05   855.5  2479.6
   895.8 2489.59   966.2 2504.15   986.4 2507.68  1006.5 2511.07  1036.7 2513.55
#Mann= 3 , 0 , 0
       0     .05       0   410.7    .045       0   425.7     .05       0
Bank Sta=410.7,425.7
XS Rating Curve= 0 ,0
Exp/Cntr=0.3,0.1

Type RM Length L Ch R = 1 ,118685  ,368.8,364.2,359.7
XS GIS Cut Line= 2
     2051890.302      294300.022     2052946.292      294662.555
#Sta/Elev= 30
       0 2557.28    60.4 2542.01    70.4 2538.68    80.5 2533.83   120.7 2523.23
   140.8 2516.42   160.9 2504.35   221.3 2475.48   231.3 2470.29   241.4 2463.66
   251.5  2460.8   271.6 2456.61   281.6 2455.76   408.9 2451.74   412.4 2451.72
   423.9 2451.83   533.1 2454.82   643.7 2455.15   724.2 2456.85   784.6  2459.8
     855 2467.34   885.1 2475.76   905.3 2485.06   975.7 2507.53   985.7  2513.3
   995.8 2516.81  1015.9  2523.2  1056.1 2533.73  1076.2 2542.78  1116.5 2556.02
#Mann= 3 , 0 , 0
       0     .05       0   408.9    .045       0   423.9     .05       0
Bank Sta=408.9,423.9
XS Rating Curve= 0 ,0
Exp/Cntr=0.3,0.1

Type RM Length L Ch R = 1 ,118320.8,521.5,526.2,530.8
XS GIS Cut Line= 2
     2051819.841      294729.604     2052861.909      294864.341
#Sta/Elev= 30
       0 2480.33      30 2475.98      60 2472.82    90.1 2471.19   130.1 2468.13
   190.1 2464.43   200.1 2462.96   210.2 2460.35   220.2 2458.58   240.2 2455.87
   290.2 2453.45   370.2 2450.72   385.2 2450.89   520.4 2452.85   680.5 2456.33
   690.5  2457.1   720.5 2461.57   750.5 2465.21   760.5 2466.77   800.6  2474.8
   830.6 2481.75   840.6  2484.6   850.6  2489.1   880.6 2496.76   920.6 2506.18
   930.7 2511.29   960.7 2519.54   990.7 2528.72  1000.7 2534.77  1050.7 2552.12
#Mann= 3 , 0 , 0
       0     .05       0   370.2    .045       0   385.2     .05       0
Bank Sta=370.2,385.2
XS Rating Curve= 0 ,0
Exp/Cntr=0.3,0.1

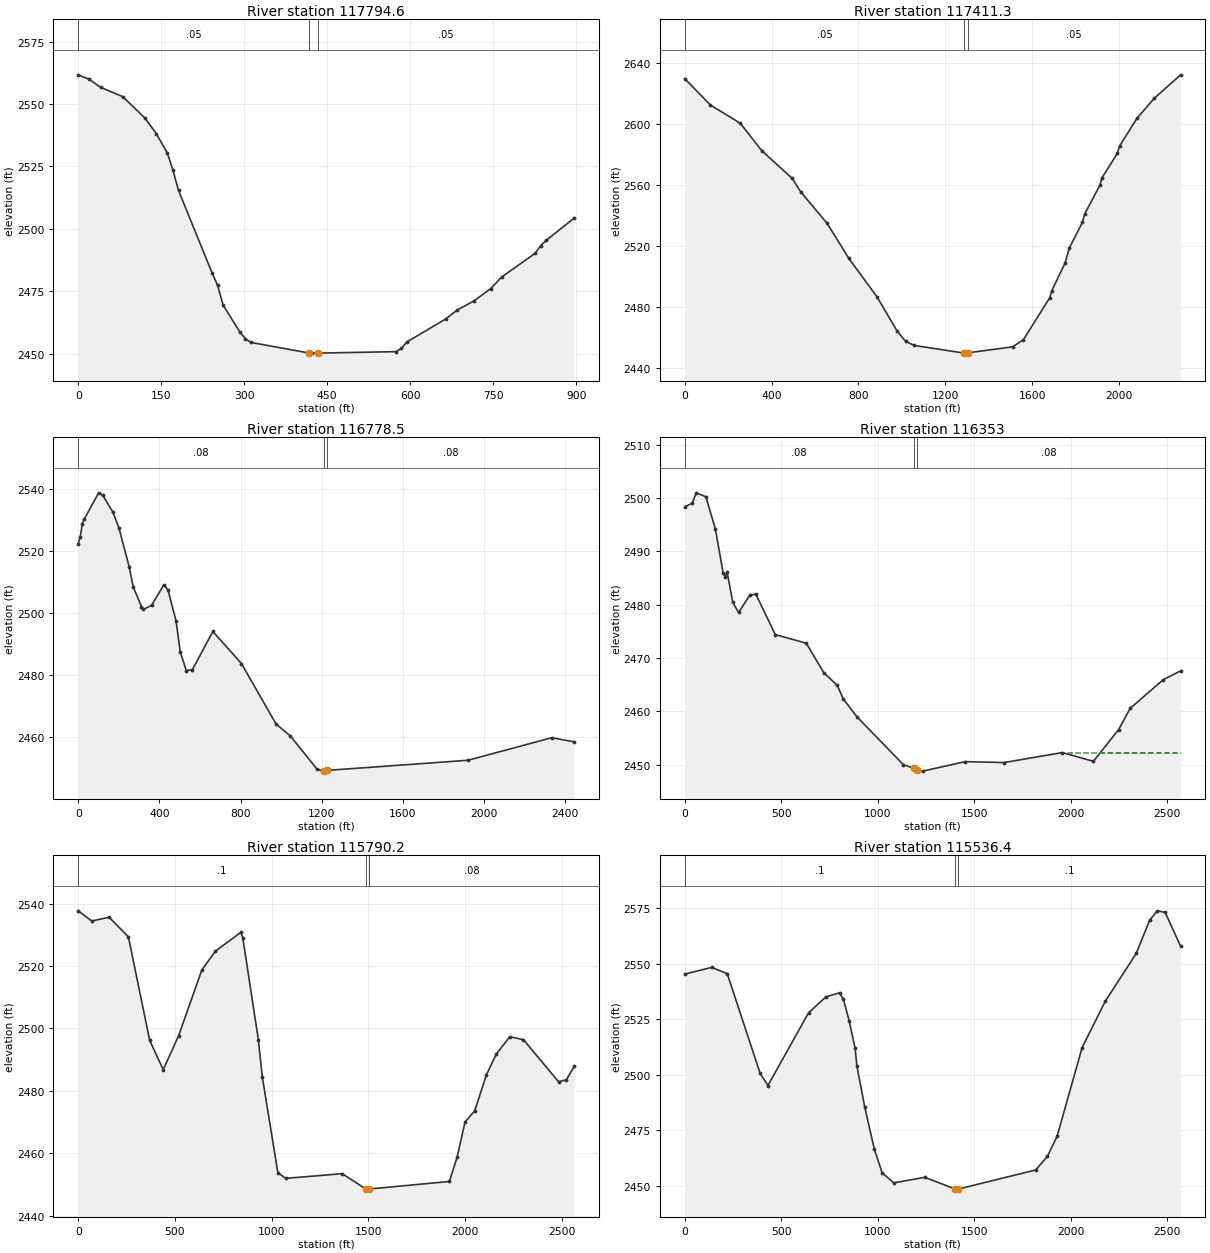
Type RM Length L Ch R = 1 ,117794.6,390.9,383.3,375.7
XS GIS Cut Line= 2
     2051767.043      295165.188     2052616.038      295452.294
#Sta/Elev= 30
       0 2561.67    20.1 2559.86    40.3 2556.67    80.6 2552.92   120.8  2544.3
     141 2538.15   161.1 2530.37   171.2 2523.47   181.3 2515.37   241.7 2482.49
   251.8 2477.49   261.8 2469.54     292 2458.75   302.1 2456.01   312.2 2454.55
   417.8 2450.29   422.9 2450.27   432.8 2450.28     574 2450.86   584.1 2452.18
   594.1 2454.75   664.6 2464.01   684.8  2467.5     715 2471.15   745.2 2476.08
   765.3 2480.75   825.7 2490.22   835.8  2493.3   845.9 2495.45   896.2 2504.32
#Mann= 3 , 0 , 0
       0     .05       0   417.8    .045       0   432.8     .05       0
Bank Sta=417.8,432.8
XS Rating Curve= 0 ,0
Exp/Cntr=0.3,0.1

Type RM Length L Ch R = 1 ,117411.3,631.3,632.6,633.9
XS GIS Cut Line= 3
     2050871.323      295681.309     2051285.547      295680.372
     2053155.534      295676.145
#Sta/Elev= 30
       0 2629.61   118.4 2612.31   256.4 2600.34     355  2582.4   494.6 2564.36
   534.9 2555.35   655.5 2534.92     756 2511.94   886.8 2486.51   977.2 2464.62
  1017.4 2457.58  1057.7  2454.9  1287.9 2449.89  1288.9 2449.88  1302.9 2450.06
  1510.1 2453.99  1560.4 2458.69    1681 2486.05    1691 2490.85  1751.4 2508.62
  1771.5 2518.66  1831.8 2535.52  1841.8 2540.84  1912.2 2559.73  1922.3 2564.72
  1992.7 2580.62  2002.7 2585.35  2083.1  2603.6  2163.6 2616.81  2284.2 2632.07
#Mann= 3 , 0 , 0
       0     .05       0  1287.9    .045       0  1302.9     .05       0
Bank Sta=1287.9,1302.9
XS Rating Curve= 0 ,0
Exp/Cntr=0.3,0.1

Type RM Length L Ch R = 1 ,116778.5,420.7,425.4,418.9
XS GIS Cut Line= 3
     2050713.847       296044.13     2051908.394      296210.583
     2053133.635      296381.313
#Sta/Elev= 30
       0  2522.3      10 2524.41    20.1  2528.7    30.2 2530.23   100.5 2538.64
   120.6 2537.86   170.9 2532.44     201 2527.22   251.3 2514.73   271.4 2508.23
   311.6 2502.01   321.6 2501.09   361.8 2502.43   422.1 2509.04   442.2 2507.36
   482.4 2497.24   502.5 2487.46   532.7 2481.32   562.8 2481.71   663.4 2493.98
   804.1 2483.64   974.9 2464.14  1045.3  2460.3  1175.9 2449.68  1206.1 2448.98
  1212.2 2449.02  1227.2 2449.22  1920.2 2452.48  2332.5 2459.74  2443.2 2458.42
#Mann= 3 , 0 , 0
       0     .08       0  1212.2    .045       0  1227.2     .08       0
Bank Sta=1212.2,1227.2
XS Rating Curve= 0 ,0
Exp/Cntr=0.3,0.1

Type RM Length L Ch R = 1 ,116353  ,545.6,562.8,505.8
XS GIS Cut Line= 3
     2050680.553      296135.904     2051068.193      296266.993
     2053115.682      296959.397
#Sta/Elev= 30
       0 2498.31    39.9 2499.05    59.9 2500.96   109.8 2500.23   159.7 2494.09
   199.6  2485.9   209.6 2485.24   219.6 2486.13   249.5  2480.4   279.5 2478.52
   339.3 2481.85   369.3 2481.93   469.5 2474.38   630.4 2472.76   720.8 2467.24
   791.2 2464.84   821.4 2462.35   891.8    2459    1133    2450    1188 2449.29
    1203    2449  1233.6 2448.77  1454.7 2450.55  1655.8 2450.38  1957.4 2452.25
  2118.2 2450.61  2248.9 2456.54  2309.2 2460.54  2480.1 2465.91  2570.6 2467.58
#Mann= 3 , 0 , 0
       0     .08       0    1188    .045       0    1203     .08       0
#XS Ineff= 2 , 0
                          1987.6         2452.25
Permanent Ineff=
       F       F
Bank Sta=1188,1203
XS Rating Curve= 0 ,0
Exp/Cntr=0.3,0.1

Type RM Length L Ch R = 1 ,115790.2,234.3,253.9,287.5
XS GIS Cut Line= 3
     2050602.398      296482.104     2051209.057      296648.725
     2053075.246      297161.279
#Sta/Elev= 30
       0 2537.68    69.9 2534.42   159.8 2535.63   259.6 2529.33   369.5 2496.18
   439.4 2486.77   519.3 2497.67   639.2 2518.73   709.8 2524.77   840.8 2530.77
   850.9 2529.08   931.5 2496.36   951.7 2484.52  1032.3 2453.77  1072.6 2451.93
  1364.9 2453.43  1486.6 2448.55    1496 2448.48  1501.6  2448.5  1919.3 2450.94
  1959.6 2458.78    2000 2469.99  2050.4 2473.59  2110.8 2485.13  2161.2  2491.7
  2231.8 2497.36  2302.4 2496.36  2483.8  2482.9  2524.1 2483.54  2564.4 2487.79
#Mann= 3 , 0 , 0
       0      .1       0  1486.6    .045       0  1501.6     .08       0
Bank Sta=1486.6,1501.6
XS Rating Curve= 0 ,0
Exp/Cntr=0.3,0.1

Type RM Length L Ch R = 1 ,115536.4,497.2,483.8,470.5
XS GIS Cut Line= 4
     2050581.782      296521.125     2051762.992        296909.2
     2052026.614      297304.633     2052859.467      297476.162
#Sta/Elev= 30
       0 2545.37   140.4 2548.41   220.6 2545.57     391 2500.59   431.2 2495.18
   641.7 2527.94     732 2535.14   802.2 2536.97   822.2 2534.04   852.3 2524.26
   882.4 2512.13   892.4 2503.82   932.5  2485.5   982.6 2466.43  1022.7 2455.88
  1082.9 2451.29  1243.3  2453.8  1402.7 2448.49  1411.6 2448.48  1417.7 2448.52
  1818.6 2457.13  1878.6 2463.22  1928.7  2472.2  2058.7 2512.27  2178.8  2533.2
  2338.8 2554.67  2408.8 2569.75  2448.9  2573.9  2488.9  2573.2  2568.9 2557.91
#Mann= 3 , 0 , 0
       0      .1       0  1402.7    .045       0  1417.7      .1       0
Bank Sta=1402.7,1417.7
XS Rating Curve= 0 ,0
Exp/Cntr=0.3,0.1

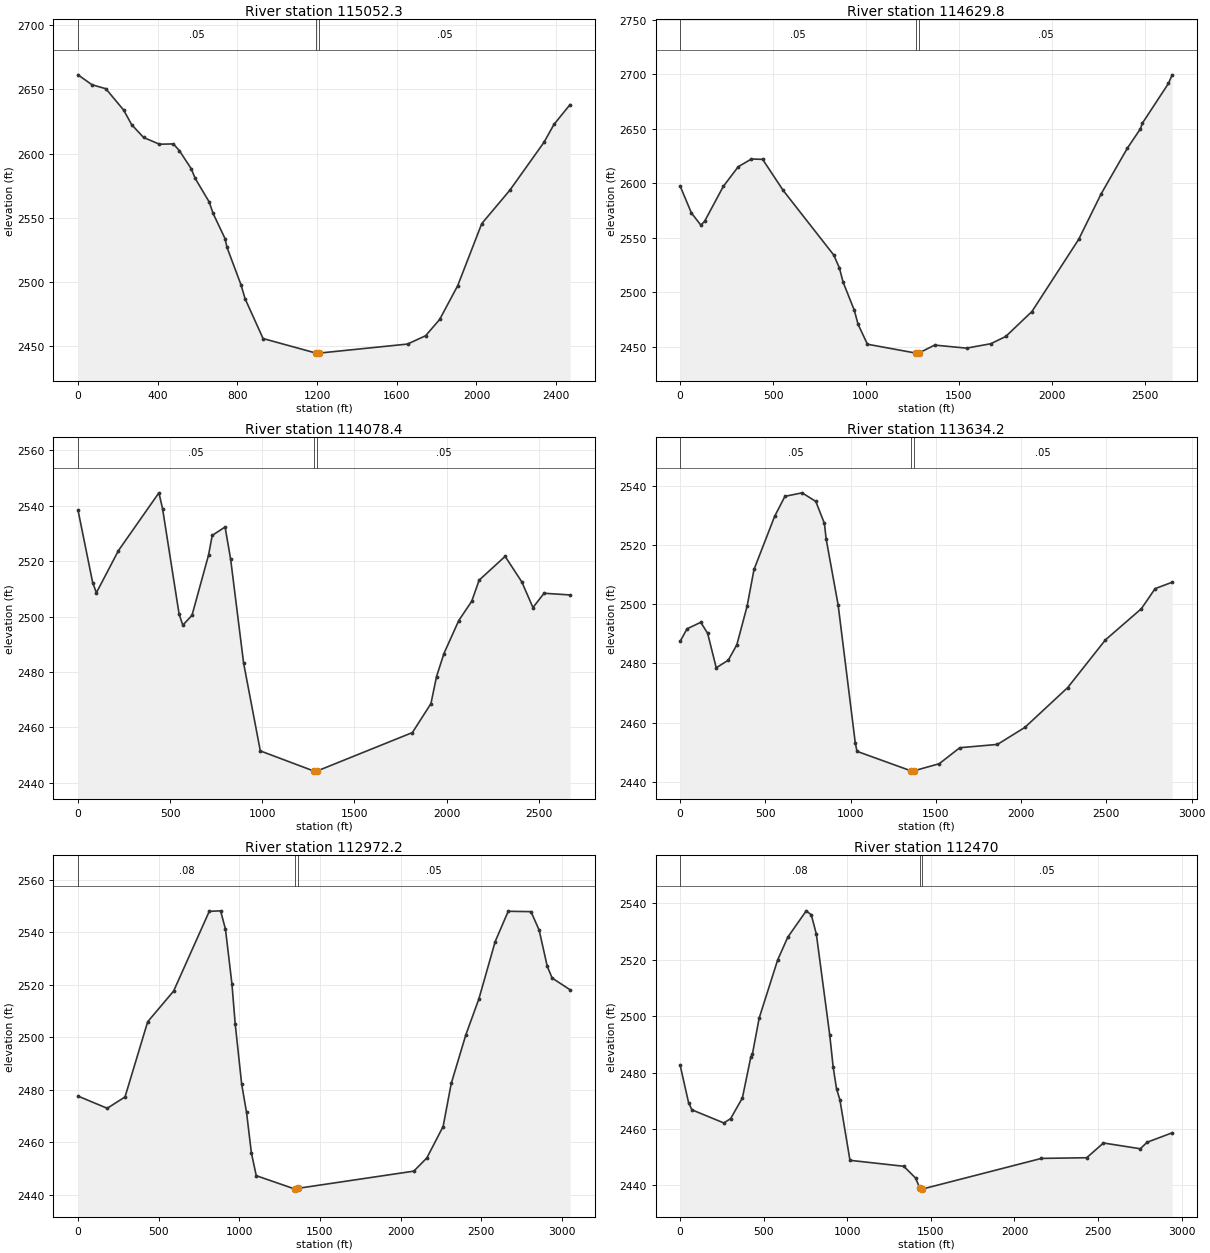
Type RM Length L Ch R = 1 ,115052.3,425.5,422.3,419.1
XS GIS Cut Line= 3
     2050408.975      296879.328     2051098.537      297168.462
      2052686.66      297834.365
#Sta/Elev= 30
       0 2661.38    69.8 2653.67   139.6 2650.55   229.3 2633.84   269.2 2622.52
     329 2612.54   408.8 2607.25   478.5  2607.5   508.4 2602.34   568.3 2588.14
   588.2 2580.58     658 2562.34   677.9 2553.34   737.8 2533.69   747.7 2526.85
   818.2 2497.55   838.4 2486.81     929 2455.66  1195.2  2444.3  1200.9 2444.29
  1210.2 2444.31  1654.1 2451.36  1744.7 2457.85  1815.2 2470.53  1905.8 2496.88
  2026.7 2545.32  2167.7 2571.39  2338.9 2608.72  2389.2 2622.71  2469.8 2638.15
#Mann= 3 , 0 , 0
       0     .05       0  1195.2    .045       0  1210.2     .05       0
Bank Sta=1195.2,1210.2
XS Rating Curve= 0 ,0
Exp/Cntr=0.3,0.1

Type RM Length L Ch R = 1 ,114629.8,548.1,551.1,553.8
XS GIS Cut Line= 3
      2050163.67      297424.972      2050778.61      297585.263
     2052726.815      298093.084
#Sta/Elev= 30
       0 2597.54    60.5 2572.89     111 2561.78   131.1 2565.11     232 2597.18
   312.7 2615.33   383.3 2622.34   443.8  2622.1   554.8 2593.51   826.8 2534.29
     857  2522.6   877.1 2509.39   937.5 2483.64   957.6  2470.8    1008 2452.45
  1269.7 2444.28  1271.5 2444.28  1286.5 2444.55  1370.3 2451.65  1541.5 2448.84
  1672.3 2452.91  1752.9 2459.58  1893.8 2482.47  2145.5  2548.7  2266.3  2590.4
  2407.2 2632.25  2477.7 2650.05  2487.7 2655.07  2628.7  2691.7  2648.8 2699.61
#Mann= 3 , 0 , 0
       0     .05       0  1271.5    .045       0  1286.5     .05       0
Bank Sta=1271.5,1286.5
XS Rating Curve= 0 ,0
Exp/Cntr=0.3,0.1

Type RM Length L Ch R = 1 ,114078.4,443.6,443.8,443.9
XS GIS Cut Line= 3
     2050019.946      297716.263     2050765.305      298028.793
     2052482.492      298748.813
#Sta/Elev= 30
       0 2538.32    79.8 2512.16    99.8 2508.58   219.5 2523.78     439 2544.59
     459 2538.85   548.8  2500.8   568.8 2496.89   618.6 2500.44   708.4 2522.16
   728.4 2529.25   798.2 2532.28   828.4 2520.63   898.8 2483.19   989.4 2451.56
  1281.3 2444.27    1282 2444.27    1297  2444.3  1814.7 2458.17  1915.4 2468.61
  1945.6 2478.31  1985.8 2486.64  2066.4 2498.56  2136.8 2505.51  2177.1 2513.12
    2318 2521.69  2408.6 2512.48    2469 2503.24  2529.4 2508.39  2670.3 2507.78
#Mann= 3 , 0 , 0
       0     .05       0    1282    .045       0    1297     .05       0
Bank Sta=1282,1297
XS Rating Curve= 0 ,0
Exp/Cntr=0.3,0.1

Type RM Length L Ch R = 1 ,113634.2,652.5,662,671.9
XS GIS Cut Line= 3
      2049649.66      297996.149     2050522.722      298362.226
      2052311.01      299112.058
#Sta/Elev= 30
       0 2487.44    40.3 2491.68   120.9 2493.87   161.1 2490.16   211.5  2478.5
     282 2481.07   332.4 2486.27   392.8 2499.37   433.1 2511.73   553.9 2529.67
   614.4 2536.44   715.1 2537.63   795.6 2534.72     846 2527.29   856.1 2522.08
   926.6  2499.7  1027.1  2453.1  1037.1 2450.27    1355 2443.65  1358.6 2443.58
    1370 2443.67  1519.4 2446.08    1640 2451.49    1861 2452.61  2021.8 2458.36
    2273 2471.82    2494 2487.92    2705 2498.47  2785.4 2505.24  2885.8 2507.42
#Mann= 3 , 0 , 0
       0     .05       0    1355    .045       0    1370     .05       0
Bank Sta=1355,1370
XS Rating Curve= 0 ,0
Exp/Cntr=0.3,0.1

Type RM Length L Ch R = 1 ,112972.2,497.7,501.3,501.3
XS GIS Cut Line= 3
     2049590.911       298057.21     2050649.044      299144.498
     2051718.708      300243.635
#Sta/Elev= 30
       0 2477.54   180.9  2472.9   291.4 2477.22     432 2505.86   592.8 2517.54
   813.8  2547.9   884.2  2548.1   914.3  2541.1   954.5 2520.22   974.6  2505.1
  1014.8 2482.07    1045 2471.33  1075.1 2455.88  1105.2 2447.23  1346.4 2442.11
    1347 2442.11    1362  2442.4  2082.2 2448.96    2163 2453.99  2263.9 2465.96
  2314.3 2482.37  2405.1 2500.93  2485.8 2514.58  2586.8  2536.4  2667.5 2547.93
  2808.7 2547.79  2859.2 2540.78  2909.6 2526.99  2939.9  2522.5  3050.9 2518.04
#Mann= 3 , 0 , 0
       0     .08       0    1347    .045       0    1362     .05       0
Bank Sta=1347,1362
XS Rating Curve= 0 ,0
Exp/Cntr=0.3,0.1

Type RM Length L Ch R = 1 ,112470  ,620.3,627.3,634.1
XS GIS Cut Line= 3
     2049307.657        298317.8     2050535.147      299579.112
     2051360.488      300427.194
#Sta/Elev= 30
       0 2482.58    50.3 2469.36    70.4  2466.8   261.5 2462.14   301.7 2463.68
   372.1    2471   422.4 2485.47   432.5  2486.7   472.7 2499.37   583.3 2519.99
   643.7 2528.05   754.3  2537.4   784.5 2535.97   814.6 2529.16   895.1 2493.19
   915.2 2482.02   935.3 2474.29   955.4 2470.39  1015.8 2448.89  1337.6 2446.78
    1408 2442.62  1433.2 2439.09  1438.2 2438.67  1448.2 2438.69  2161.2 2449.57
  2431.9 2449.81  2532.2 2455.04  2752.9 2452.99    2793 2455.29  2943.4 2458.65
#Mann= 3 , 0 , 0
       0     .08       0  1433.2    .045       0  1448.2     .05       0
Bank Sta=1433.2,1448.2
XS Rating Curve= 0 ,0
Exp/Cntr=0.3,0.1

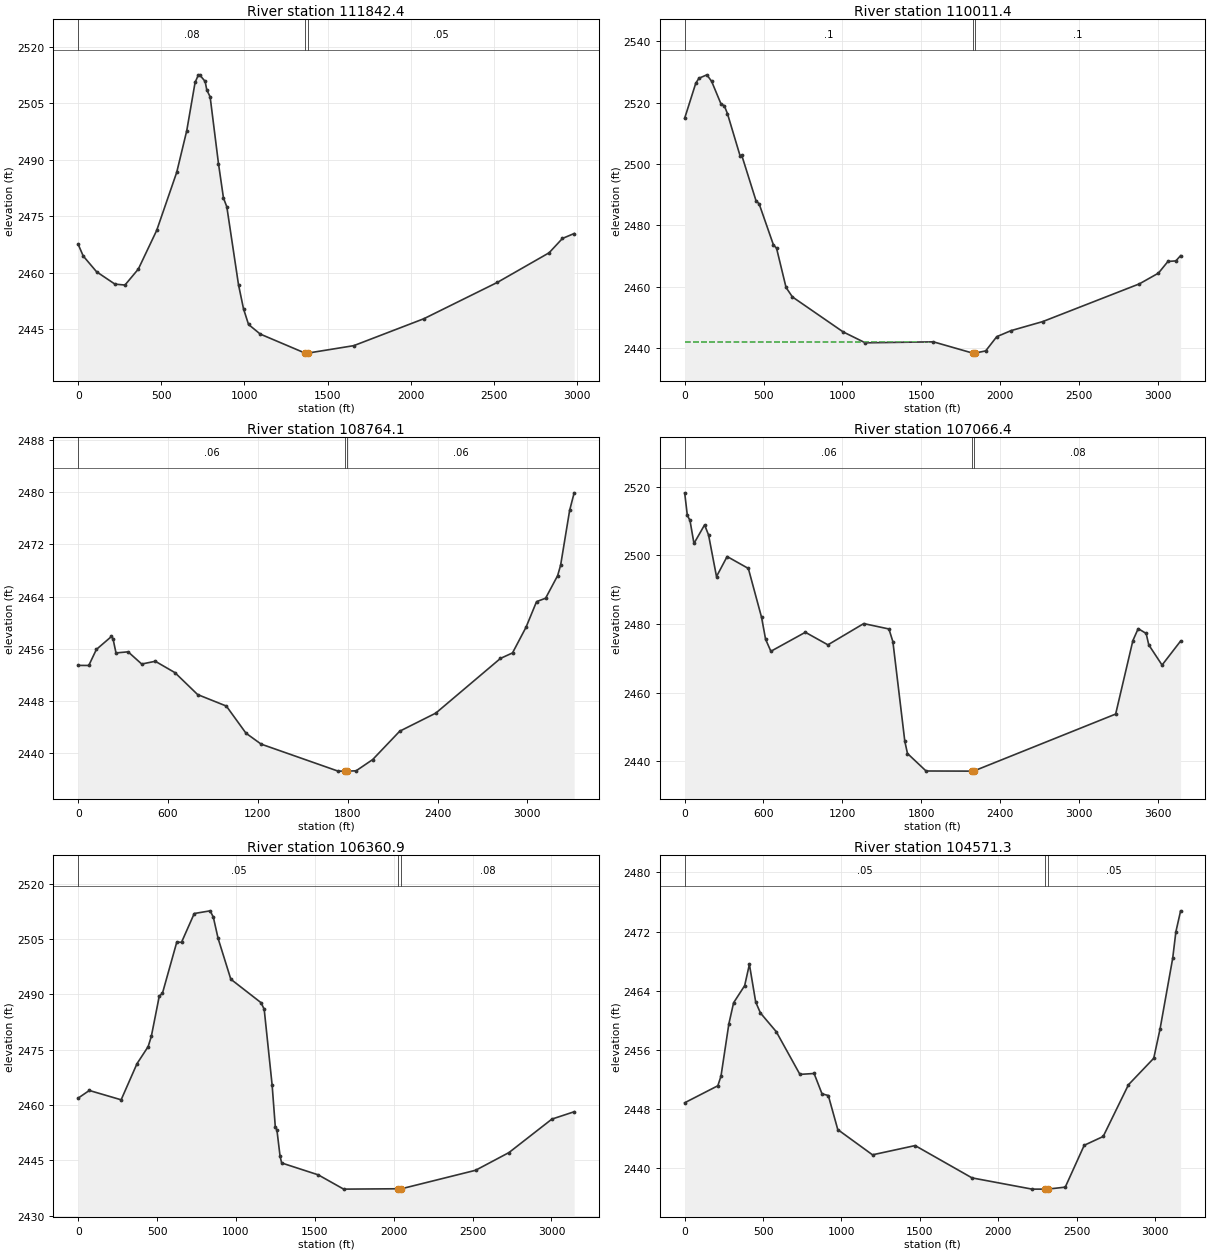
Type RM Length L Ch R = 1 ,111842.4,1857.4,1828.1,1819.4
XS GIS Cut Line= 3
     2049207.572      298412.385     2050003.345      299865.896
     2050639.988       301028.75
#Sta/Elev= 30
       0 2467.53    30.1 2464.45   110.5 2460.26     221 2456.98   281.2 2456.74
   361.6 2460.98     472 2471.24   592.5 2486.66   652.8 2497.71     703 2510.53
   723.1 2512.53   733.1 2512.38   763.3 2510.79   773.3 2508.52   793.4 2506.69
   843.6 2488.98   873.7 2479.82   893.8  2477.5   964.1 2456.82   994.2 2450.43
  1024.4 2446.28  1094.7 2443.73  1364.9 2438.67  1379.9 2438.67  1657.1 2440.65
  2078.9  2447.8  2520.8 2457.44  2832.2  2465.3  2912.5 2469.11  2982.8 2470.41
#Mann= 3 , 0 , 0
       0     .08       0  1364.9    .045       0  1379.9     .05       0
Bank Sta=1364.9,1379.9
XS Rating Curve= 0 ,0
Exp/Cntr=0.3,0.1

Type RM Length L Ch R = 1 ,110011.4,1244.8,1246.4,1256
XS GIS Cut Line= 3
     2048249.387      298540.131     2049010.374      299805.042
     2049870.096      301234.069
#Sta/Elev= 30
       0 2514.93    70.3 2526.34    90.4 2527.95   140.6 2529.07   170.7 2526.96
     231 2519.49     251 2519.02   271.1 2516.43   351.5 2502.63   361.5 2502.89
   451.9 2488.09     472 2487.02   562.4 2473.68   582.4 2472.56   642.7 2459.76
   682.9 2456.69  1004.2  2445.3  1144.8 2441.73  1576.6 2442.05  1826.3 2438.37
  1841.3 2438.39  1908.2  2439.1  1978.5 2443.74  2068.9  2445.7  2269.8 2448.65
  2882.7 2460.95  3003.2 2464.44  3063.5 2468.25  3113.7 2468.43  3143.9 2470.15
#Mann= 3 , 0 , 0
       0      .1       0  1826.3    .045       0  1841.3      .1       0
#XS Ineff= 2 , 0
         1547.18 2442.15
Permanent Ineff=
       F       F
Bank Sta=1826.3,1841.3
XS Rating Curve= 0 ,0
Exp/Cntr=0.3,0.1

Type RM Length L Ch R = 1 ,108764.1,1721.1,1694.5,1682
XS GIS Cut Line= 3
     2047944.474      298578.793     2048587.302      300016.786
     2049296.474       301603.19
#Sta/Elev= 30
       0 2453.47    70.7 2453.46   121.2 2455.91   222.1  2457.9   232.2 2457.58
   252.4 2455.38   333.2 2455.55   424.1 2453.68     515  2454.1   646.2 2452.36
   797.7    2449   989.5 2447.24  1120.8 2443.08  1221.7 2441.41  1735.8 2437.27
  1783.1 2437.27  1798.1 2437.27  1856.4 2437.32  1966.9 2439.04  2147.7 2443.39
  2388.7 2446.16  2820.6 2454.54    2901 2455.38  2991.4 2459.32  3061.7 2463.24
    3122 2463.76  3202.4 2467.22  3222.4 2468.82  3282.7 2477.23  3312.8 2479.91
#Mann= 3 , 0 , 0
       0     .06       0  1783.1    .045       0  1798.1     .06       0
Bank Sta=1783.1,1798.1
XS Rating Curve= 0 ,0
Exp/Cntr=0.3,0.1

Type RM Length L Ch R = 1 ,107066.4,728.2,706.7,704.5
XS GIS Cut Line= 3
     2046690.812      298953.744     2048094.482      300461.235
     2049263.844      301717.088
#Sta/Elev= 30
       0 2518.24    20.2 2511.66    40.4  2510.2    70.7  2503.5   151.5  2508.9
   181.8 2505.97   242.3 2493.85   323.1 2499.69   484.7 2496.22   585.6 2481.94
   615.9  2475.6   656.3 2472.09   918.8 2477.63  1090.5 2473.97  1363.1 2480.16
    1555 2478.59  1585.2 2474.89  1676.1 2445.84  1696.3 2442.32  1837.7 2437.23
  2180.9 2437.19  2189.1 2437.25  2204.1 2437.27  3281.2 2453.81  3412.4 2475.21
  3452.8 2478.69  3513.3 2477.29  3533.5 2473.95  3634.5 2468.08  3775.8 2475.08
#Mann= 3 , 0 , 0
       0     .06       0  2189.1    .045       0  2204.1     .08       0
Bank Sta=2189.1,2204.1
XS Rating Curve= 0 ,0
Exp/Cntr=0.3,0.1

Type RM Length L Ch R = 1 ,106360.9,1684.3,1788.8,1805.4
XS GIS Cut Line= 2
     2046588.633      299354.873     2048682.513      301700.153
#Sta/Elev= 30
       0 2461.85    70.5 2463.91   272.1 2461.38   372.8 2471.18   443.4  2475.8
   463.5 2478.58   513.9 2489.47   534.1 2490.27   624.8 2504.11     655 2504.08
   735.6 2511.87   836.4  2512.6   856.5 2510.89   886.8 2505.13   967.4 2494.07
  1158.8 2487.71    1179 2485.93  1229.4 2465.35  1249.5    2454  1259.6 2453.23
  1279.8 2446.04  1289.8 2444.26  1521.6 2441.04  1682.8 2437.17  2030.2 2437.27
  2045.2 2437.23  2519.2 2442.28  2730.8 2447.08  3002.9 2456.15    3144 2458.14
#Mann= 3 , 0 , 0
       0     .05       0  2030.2    .045       0  2045.2     .08       0
Bank Sta=2030.2,2045.2
XS Rating Curve= 0 ,0
Exp/Cntr=0.3,0.1

Type RM Length L Ch R = 1 ,104571.3,1272.6,1260.3,1239.8
XS GIS Cut Line= 3
     2046379.888      299483.028     2046982.644      300878.709
     2048071.071      302109.505
#Sta/Elev= 30
       0 2448.85   211.4 2451.15   231.6 2452.45   281.9 2459.53   312.1 2462.38
   382.6 2464.69   412.8 2467.57   453.1 2462.47   483.3 2460.99     584 2458.47
     735 2452.69   825.6 2452.81   875.9 2450.06   916.2 2449.83   976.6 2445.22
  1198.1 2441.81  1469.9 2443.06  1832.8 2438.69  2215.8 2437.17  2300.7 2437.17
  2315.7 2437.17  2427.5 2437.44  2548.4  2443.1  2669.4 2444.29  2830.7 2451.29
  2991.9 2454.87  3032.3 2458.85  3112.9 2468.41  3133.1 2471.98  3163.3 2474.81
#Mann= 3 , 0 , 0
       0     .05       0  2300.7    .045       0  2315.7     .05       0
Bank Sta=2300.7,2315.7
XS Rating Curve= 0 ,0
Exp/Cntr=0.3,0.1

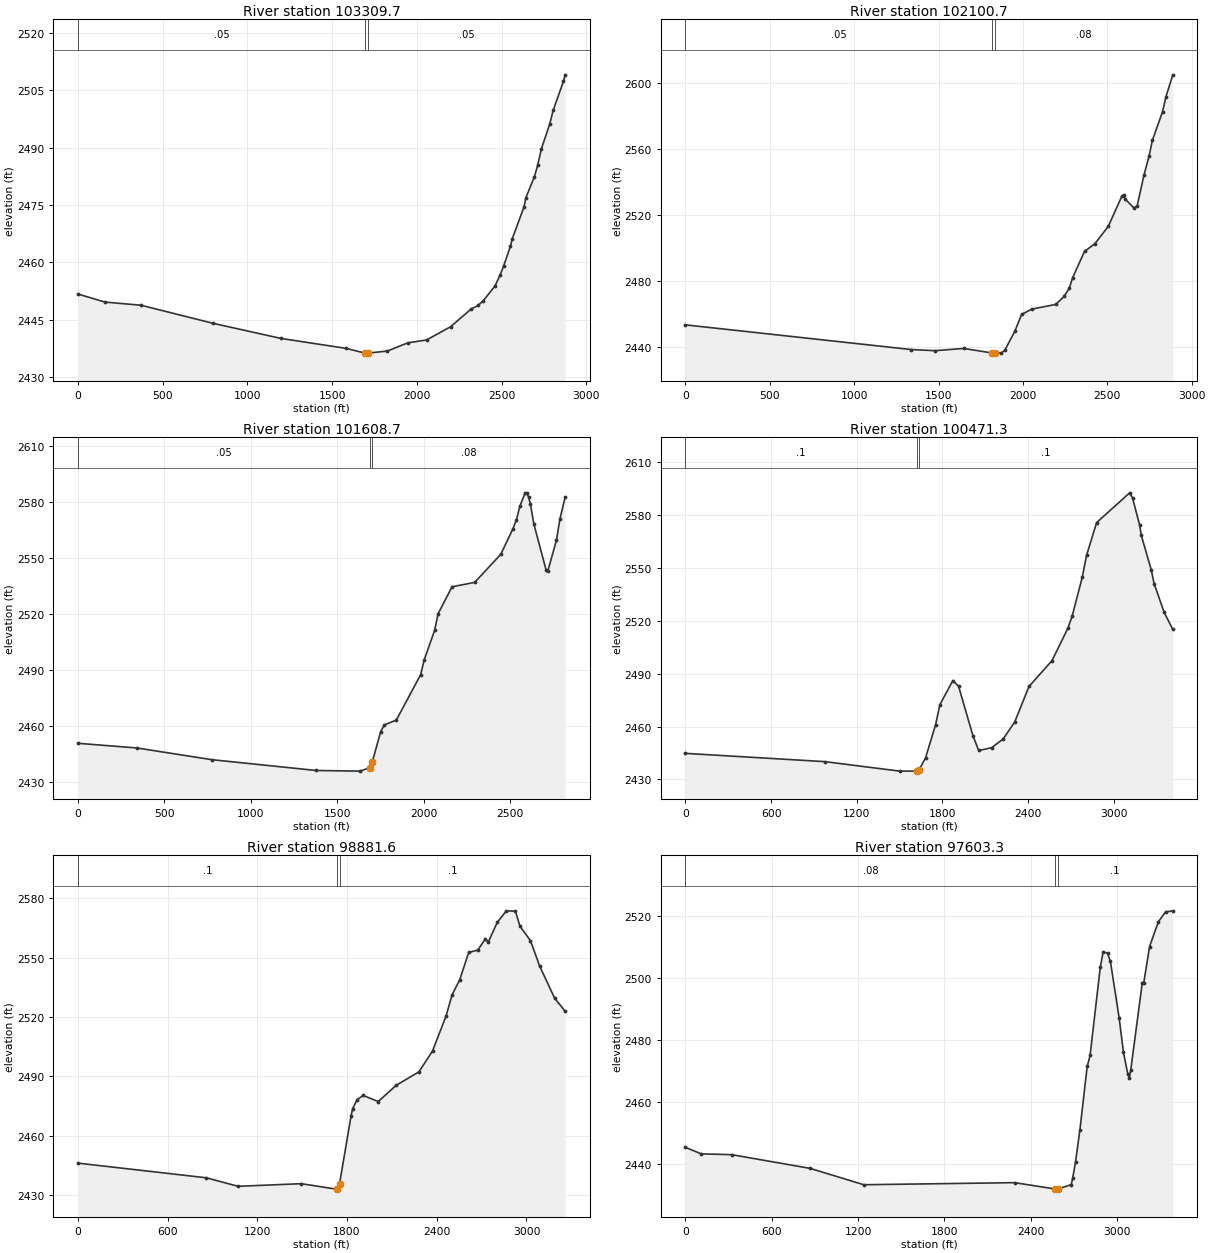
Type RM Length L Ch R = 1 ,103309.7,1215.5,1209.1,1195
XS GIS Cut Line= 3
     2045401.882      301732.536      2045479.77      301752.028
     2048190.973      302430.496
#Sta/Elev= 30
       0 2451.74     161 2449.62   372.9  2448.8   796.6 2444.08  1200.2  2440.1
  1583.6 2437.51  1694.6 2436.27  1695.3 2436.27  1710.3 2436.27  1825.8 2436.81
  1946.9 2438.96  2057.8 2439.72  2199.1 2443.17  2320.2  2447.8  2360.5 2448.73
  2390.8 2449.92  2461.4 2453.85  2491.7 2456.74  2511.9 2459.05  2552.2 2464.24
  2562.3 2466.11    2633 2474.62    2643 2476.89  2693.5 2482.39  2713.7 2485.56
  2733.8 2489.56  2784.3 2496.27  2804.5  2499.8    2865  2507.4  2875.1 2509.07
#Mann= 3 , 0 , 0
       0     .05       0  1695.3    .045       0  1710.3     .05       0
Bank Sta=1695.3,1710.3
XS Rating Curve= 0 ,0
Exp/Cntr=0.3,0.1

Type RM Length L Ch R = 1 ,102100.7,527.2,491.9,475.8
XS GIS Cut Line= 2
     2045310.293      302411.531     2048153.216      302921.334
#Sta/Elev= 30
       0 2453.27  1338.5 2438.28  1479.4  2437.6  1650.4 2438.95  1819.6 2436.15
  1821.5 2436.11  1834.6 2436.15  1871.8 2436.24    1892 2437.72  1952.4 2449.45
  1992.6 2459.66    2053 2462.84  2193.9 2465.67  2244.2 2470.52  2274.4 2475.42
  2294.5 2481.87    2365 2497.88  2425.3 2502.44  2505.8 2513.05  2586.4 2531.41
  2596.4 2531.97  2606.5 2529.65  2656.8 2524.35  2676.9 2525.44  2717.2  2544.1
  2747.4  2555.7  2767.5 2565.42  2827.9 2582.84    2848 2591.94  2888.3 2605.11
#Mann= 3 , 0 , 0
       0     .05       0  1819.6    .045       0  1834.6     .08       0
Bank Sta=1819.6,1834.6
XS Rating Curve= 0 ,0
Exp/Cntr=0.3,0.1

Type RM Length L Ch R = 1 ,101608.7,934.8,1137.3,1138.3
XS GIS Cut Line= 2
      2045314.05      303101.767     2048131.576      303202.652
#Sta/Elev= 30
       0 2450.78   342.4 2448.27   775.3    2442  1379.5 2436.21  1631.2 2435.87
  1688.6 2437.64  1703.6  2440.8    1752 2456.98  1772.2 2460.53  1842.6 2463.23
  1983.6 2487.59  2003.7 2495.39  2064.2  2511.3  2084.3 2520.16  2164.8  2534.6
  2295.7 2536.94  2446.8 2551.98  2517.3 2565.67  2537.4 2570.44  2557.5 2577.83
  2587.7 2584.84  2597.8  2584.9  2607.9 2582.56    2618 2578.97  2638.1 2568.21
  2708.6 2543.65  2718.6 2542.87    2769 2559.62  2789.1 2570.99  2819.3 2582.61
#Mann= 3 , 0 , 0
       0     .05       0  1688.6    .045       0  1703.6     .08       0
Bank Sta=1688.6,1703.6
XS Rating Curve= 0 ,0
Exp/Cntr=0.3,0.1

Type RM Length L Ch R = 1 ,100471.3,1752.8,1589.7,1575.9
XS GIS Cut Line= 2
     2045371.206      303776.207     2048784.777      303737.242
#Sta/Elev= 30
       0 2444.76   976.8 2440.06  1500.5 2434.67    1622  2434.7    1637 2435.49
  1681.7 2442.14  1752.2 2460.98  1782.4 2472.39    1873 2486.12  1913.3 2482.84
    2014 2454.76  2054.3 2446.39    2145 2447.98  2225.5 2452.93  2306.1 2462.51
  2406.8 2482.79  2567.9 2497.44  2678.7 2515.76  2708.9 2522.68  2779.4 2544.67
  2809.6 2557.16  2880.1 2575.78  3111.7 2592.69  3131.8 2589.79  3182.2 2574.17
  3192.2 2568.79  3262.7 2548.98  3282.9 2541.16  3353.4 2524.76  3413.8 2515.12
#Mann= 3 , 0 , 0
       0      .1       0    1622    .045       0    1637      .1       0
Bank Sta=1622,1637
XS Rating Curve= 0 ,0
Exp/Cntr=0.3,0.1

Type RM Length L Ch R = 1 ,98881.6 ,1276.3,1278.3,1272.2
XS GIS Cut Line= 3
     2046094.469       305477.67     2046452.871      305265.847
     2048899.999      303819.543
#Sta/Elev= 30
       0 2446.25   859.8 2438.83  1071.5 2434.54  1494.9 2435.86  1726.7 2433.11
  1735.2 2433.12  1750.2 2435.81  1827.5 2470.17  1837.6 2473.75  1867.8  2478.3
  1908.2 2480.42    2009 2477.34  2129.9  2485.6  2281.1 2492.35  2371.8 2502.84
  2462.6 2520.57  2502.9 2531.33  2553.3 2538.73  2613.8 2552.64  2674.2 2553.83
  2724.6 2559.36  2744.8 2557.91  2805.3 2567.89  2865.8 2573.66  2926.2 2573.47
  2956.5 2565.91    3027 2558.58  3087.5 2545.89  3188.3 2529.56  3258.9 2522.94
#Mann= 3 , 0 , 0
       0      .1       0  1735.2    .045       0  1750.2      .1       0
Bank Sta=1735.2,1750.2
XS Rating Curve= 0 ,0
Exp/Cntr=0.3,0.1

Type RM Length L Ch R = 1 ,97603.3 ,1526.8,1405.5,1401.1
XS GIS Cut Line= 3
     2047031.661      306537.113      2047520.74      305934.885
     2049168.056       303906.46
#Sta/Elev= 30
       0 2445.27   110.8 2443.17   322.4 2442.91   866.6 2438.49  1239.9  2433.2
  2289.2 2433.87  2572.7 2431.81  2581.8 2431.78  2587.7  2431.8  2682.6 2433.24
  2692.7 2435.32  2712.9 2440.68  2743.2    2451  2793.6 2471.42  2813.8 2474.98
  2884.4 2503.41  2904.6 2508.48  2934.9    2508    2955 2505.39  3015.6 2487.14
  3045.8 2475.95  3076.1 2468.93  3086.2 2467.76  3096.3  2470.2    3177 2498.54
  3187.1 2498.48  3227.5 2510.17    3288 2518.11  3338.4 2521.36  3388.9  2521.7
#Mann= 3 , 0 , 0
       0     .08       0  2572.7    .045       0  2587.7      .1       0
Bank Sta=2572.7,2587.7
XS Rating Curve= 0 ,0
Exp/Cntr=0.3,0.1