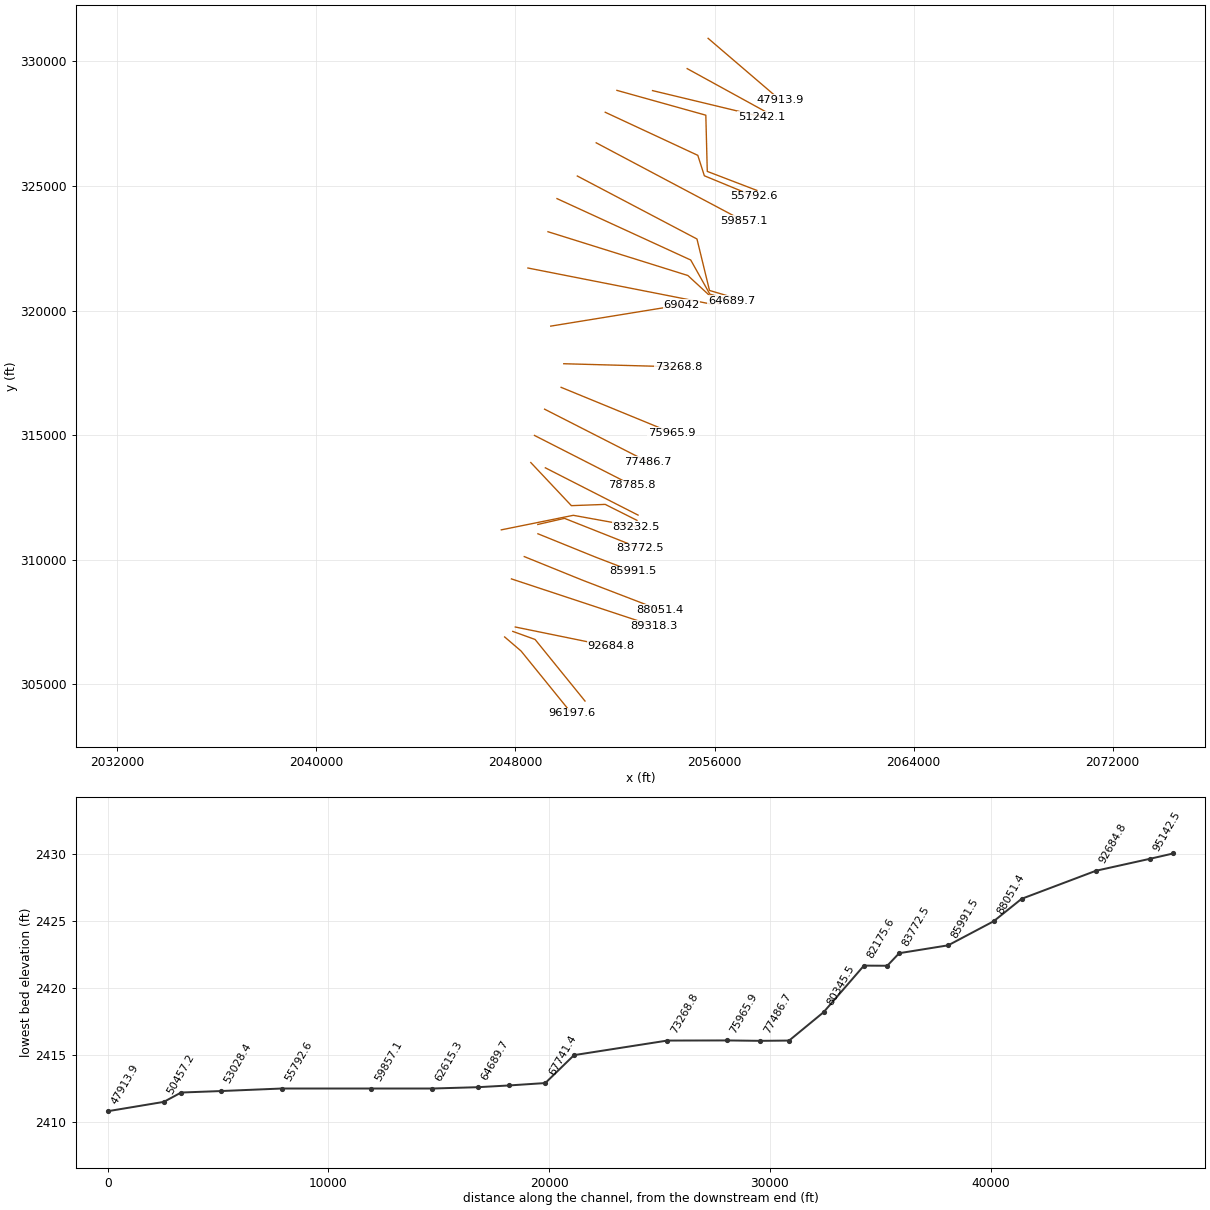
HEC-RAS study MeadowRv2.prj: MeadowRv2

--- MeadowRv2.g01 (geometry) --- (continued)

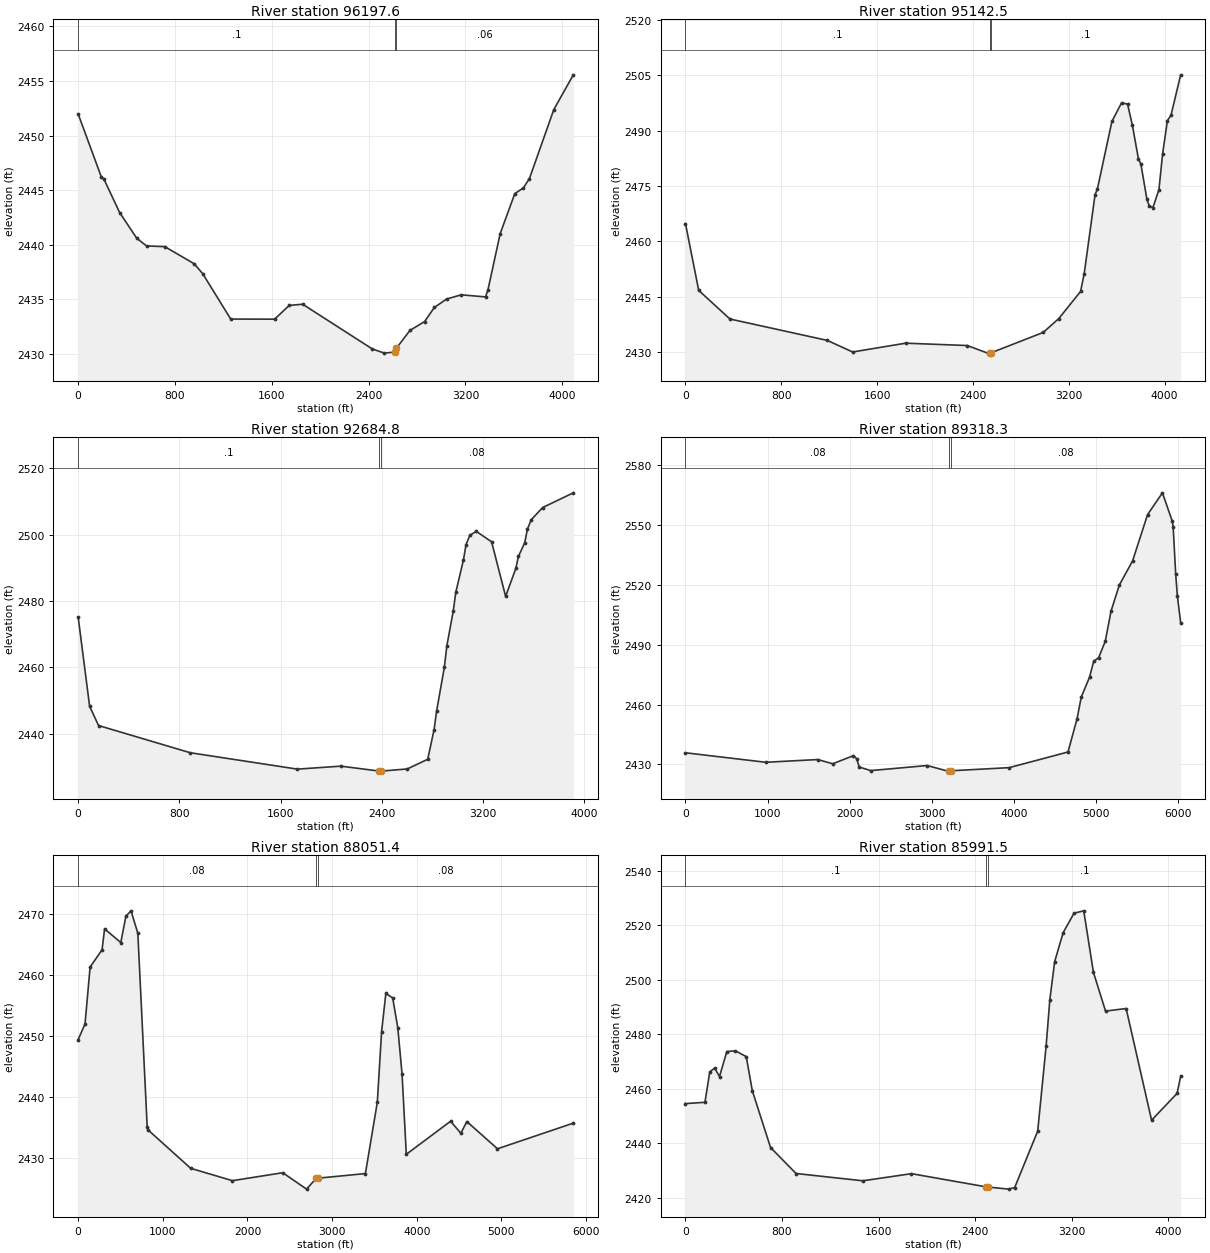
Type RM Length L Ch R = 1 ,96197.6 ,949,1055.1,1053.5
XS GIS Cut Line= 3
     2047565.793      306904.674     2048225.249      306341.221
     2050257.508      303838.796
#Sta/Elev= 30
       0 2451.97   191.6  2446.2   211.8 2446.03   342.9 2442.94   484.1 2440.59
   564.8 2439.89   716.1 2439.82     958 2438.26  1028.6 2437.35  1260.3 2433.19
  1622.9 2433.18  1743.8 2434.44  1854.6 2434.55  2428.9 2430.46  2529.6 2430.07
  2613.6 2430.17  2628.6 2430.51  2741.2 2432.15    2862 2432.96  2942.6 2434.25
  3043.4 2435.02  3164.3 2435.41  3365.8 2435.22  3385.9 2435.88  3486.6 2441.01
  3607.5 2444.68    3678  2445.2  3728.4 2446.06  3929.9 2452.38  4091.1 2455.56
#Mann= 3 , 0 , 0
       0      .1       0  2613.6    .045       0  2628.6     .06       0
Bank Sta=2613.6,2628.6
XS Rating Curve= 0 ,0
Exp/Cntr=0.3,0.1

Type RM Length L Ch R = 1 ,95142.5 ,2435.5,2457.4,2442.1
XS GIS Cut Line= 3
     2047893.646      307127.432     2048789.315      306803.735
     2050795.004      304334.026
#Sta/Elev= 30
       0 2464.79   110.3 2446.69   370.9 2438.93  1183.9 2433.12  1395.4 2429.98
  1838.4 2432.37  2351.8 2431.73    2523 2429.67  2539.5 2429.68  2554.5  2429.8
  2986.1 2435.28    3117 2439.06  3298.3  2446.4  3328.5 2451.19  3419.1 2472.63
  3439.2 2474.26    3560 2492.52  3640.6 2497.59  3690.9  2497.2  3731.2 2491.44
  3781.5 2482.32  3801.7 2481.01    3852 2471.43  3872.1 2469.57  3902.4 2469.16
  3952.7 2474.05  3982.9 2483.64  4023.2 2492.76  4053.4 2494.22  4133.9 2505.17
#Mann= 3 , 0 , 0
       0      .1       0  2539.5    .045       0  2554.5      .1       0
Bank Sta=2539.5,2554.5
XS Rating Curve= 0 ,0
Exp/Cntr=0.3,0.1

Type RM Length L Ch R = 1 ,92684.8 ,3361.1,3366.3,3390.8
XS GIS Cut Line= 3
     2047994.321      307303.536     2048940.504      307110.571
     2051828.463      306521.603
#Sta/Elev= 30
       0 2475.12    90.5  2448.3   160.9  2442.5   885.2 2434.31  1732.8 2429.37
    2076 2430.27  2377.9 2428.79  2388.9 2428.77  2392.9 2428.77  2600.9 2429.43
  2762.4 2432.34  2812.8 2441.29    2833 2446.96  2893.6    2460  2913.8 2466.56
  2964.2 2476.98  2984.4 2482.64    3045 2492.42  3065.2    2497  3095.5 2499.77
  3145.9 2500.96  3267.1 2497.81  3378.1 2481.38  3458.8 2489.82    3479  2493.4
  3529.5 2497.59  3549.7 2501.56    3580 2504.44  3670.8 2508.14  3913.1 2512.56
#Mann= 3 , 0 , 0
       0      .1       0  2377.9    .045       0  2392.9     .08       0
Bank Sta=2377.9,2392.9
XS Rating Curve= 0 ,0
Exp/Cntr=0.3,0.1

Type RM Length L Ch R = 1 ,89318.3 ,1270.6,1266.5,1272.6
XS GIS Cut Line= 3
     2047838.615      309233.367     2049578.493      308658.978
     2053562.563      307343.708
#Sta/Elev= 30
       0 2435.85   976.5  2431.1  1610.8 2432.47    1792 2430.35    2044 2434.41
  2084.4 2432.86  2114.6 2428.72  2255.8 2426.94  2941.6 2429.47  3193.8 2426.67
    3212 2426.74    3227 2426.84  3940.1 2428.41  4656.2 2436.24  4767.1 2452.95
  4817.5  2463.7  4918.4 2473.64  4968.8 2481.62  5029.3 2483.45    5110 2491.65
  5180.6 2506.79  5281.5 2519.83  5442.8  2531.9  5624.4 2555.01  5805.9 2565.96
    5927 2551.62    5937 2548.61  5967.3  2525.3  5987.5  2514.4  6027.8 2501.03
#Mann= 3 , 0 , 0
       0     .08       0    3212    .045       0    3227     .08       0
Bank Sta=3212,3227
XS Rating Curve= 0 ,0
Exp/Cntr=0.3,0.1

Type RM Length L Ch R = 1 ,88051.4 ,2055.4,2059.8,2065.9
XS GIS Cut Line= 3
     2048354.661      310128.306     2050679.023      309188.074
     2053799.986      307990.593
#Sta/Elev= 30
       0 2449.43    80.6 2451.94     141 2461.26     282 2464.08   312.2  2467.5
   503.5 2465.27   563.9 2469.57   624.3 2470.45   704.9 2466.79   815.6 2435.11
   825.7 2434.66  1329.2 2428.39  1822.6 2426.37  2416.7 2427.67  2698.6 2424.99
  2812.9 2426.77  2827.9 2426.77  3393.4 2427.53  3534.3 2439.18  3584.7  2450.7
    3635 2456.96  3715.6 2456.23    3776 2451.37  3826.3 2443.82  3876.7 2430.68
  4400.2 2436.08  4521.1 2434.11  4591.6 2436.03    4954 2431.58  5850.1 2435.77
#Mann= 3 , 0 , 0
       0     .08       0  2812.9    .045       0  2827.9     .08       0
Bank Sta=2812.9,2827.9
XS Rating Curve= 0 ,0
Exp/Cntr=0.3,0.1

Type RM Length L Ch R = 1 ,85991.5 ,2210.1,2219.3,2217.7
XS GIS Cut Line= 3
     2048902.996      311043.863     2051207.981      310111.469
     2052716.929      309532.501
#Sta/Elev= 30
       0 2454.57   161.1 2455.04   201.3 2466.23   241.6 2467.55   281.9  2464.5
   342.3 2473.66   412.7 2473.94   503.3 2471.81   553.7 2459.27   704.7 2438.46
     916 2428.92  1469.7 2426.25  1872.4 2428.86  2491.3 2424.02  2506.3 2423.96
  2677.2 2423.19  2727.4 2423.77  2918.1 2444.46  2988.4 2475.88  3018.5  2492.6
  3058.6 2506.62  3128.9 2517.27  3219.2 2524.43  3299.6 2525.29  3379.9 2502.73
  3480.2 2488.51  3650.9 2489.45  3861.7 2448.48  4072.5 2458.29  4102.6 2464.57
#Mann= 3 , 0 , 0
       0      .1       0  2491.3    .045       0  2506.3      .1       0
Bank Sta=2491.3,2506.3
XS Rating Curve= 0 ,0
Exp/Cntr=0.3,0.1

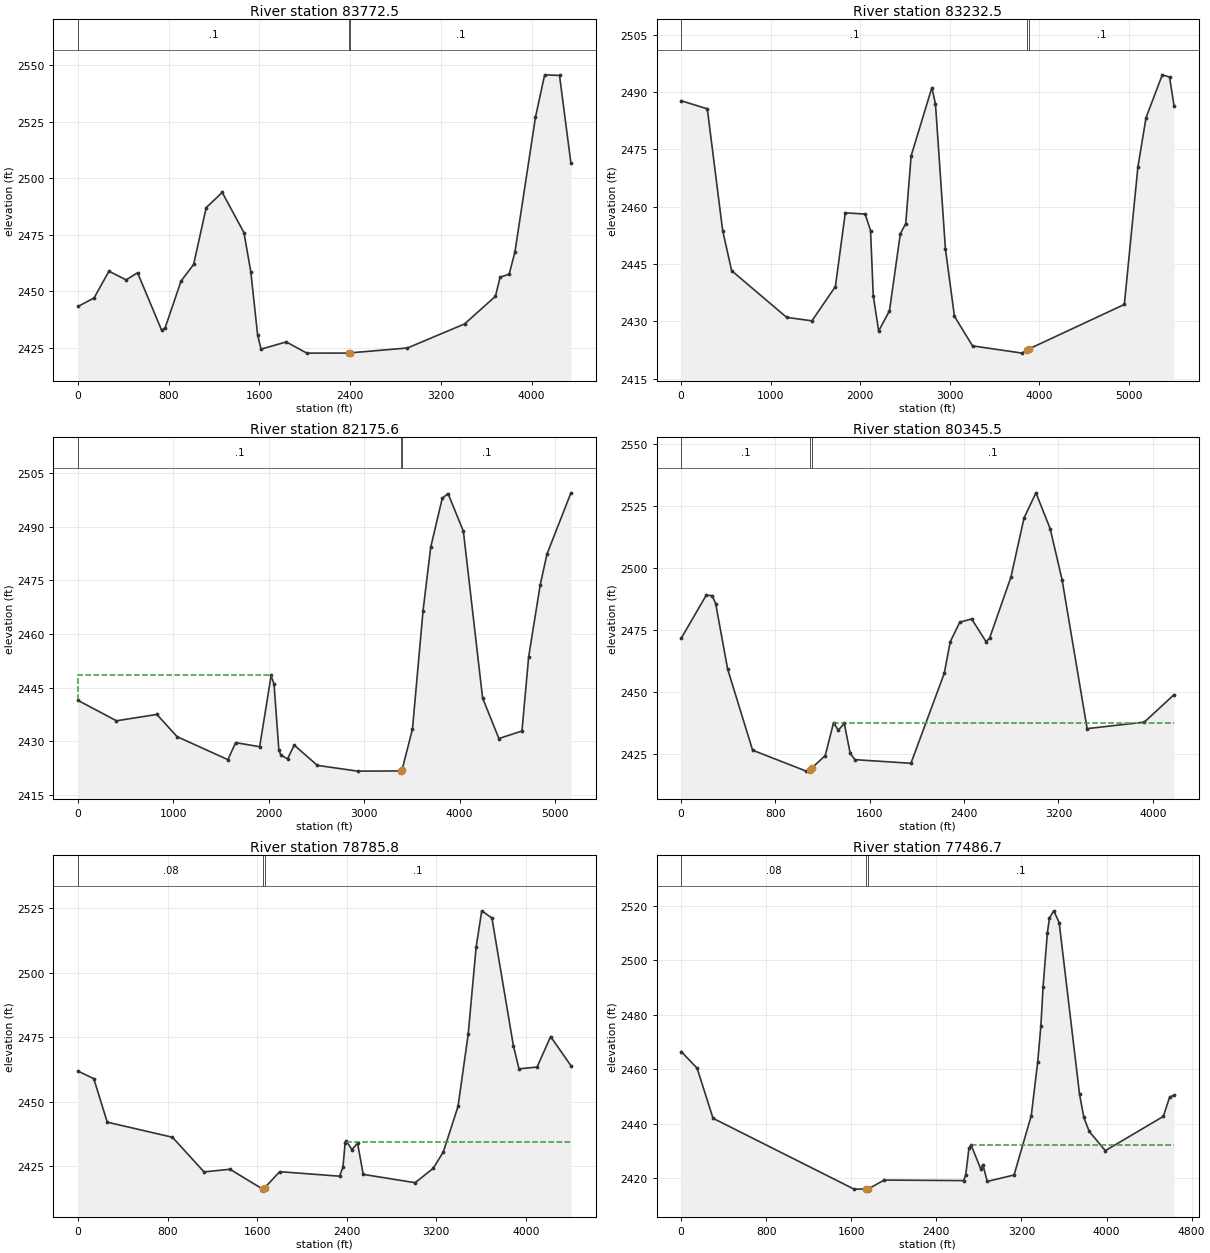
Type RM Length L Ch R = 1 ,83772.5 ,541.7,539.4,538.2
XS GIS Cut Line= 3
     2048899.489      311417.674     2049971.716      311662.217
     2052990.884      310467.718
#Sta/Elev= 30
       0 2443.26   141.2 2446.99   272.4 2458.83   423.8    2455   524.7 2458.13
   736.5 2432.78   766.8 2433.65   908.1 2454.46    1019 2461.81    1130 2486.93
  1271.2 2493.66  1462.8 2475.91  1523.3 2458.62  1583.8 2430.48    1614 2424.36
  1835.8 2427.56  2017.4 2422.61  2387.2 2422.62  2390.4  2422.6  2402.2 2422.73
  2904.7 2424.87  3408.9 2435.52  3681.1 2447.75  3721.5 2456.15  3802.1 2457.55
  3852.6 2467.32    4034 2526.98  4114.7 2545.66  4245.8  2545.4  4346.6 2506.51
#Mann= 3 , 0 , 0
       0      .1       0  2387.2    .045       0  2402.2      .1       0
Bank Sta=2387.2,2402.2
XS Rating Curve= 0 ,0
Exp/Cntr=0.3,0.1

Type RM Length L Ch R = 1 ,83232.5 ,1051.4,1056.8,1059.4
XS GIS Cut Line= 3
     2047432.229      311201.347     2050325.105      311784.322
     2052837.749      311329.367
#Sta/Elev= 30
       0 2487.74   292.1 2485.63   463.3 2453.76     564 2443.24  1178.4 2431.02
  1460.4 2430.12  1722.3 2439.09  1833.1  2458.4  2054.6 2458.07  2115.1 2453.74
  2145.3 2436.74  2205.7 2427.44  2326.6 2432.77  2447.4 2452.88  2507.9 2455.59
  2568.3 2473.31    2800 2491.19  2840.2 2486.89    2951 2448.97    3052 2431.32
  3253.8 2423.56  3808.9 2421.66  3867.1 2422.59  3882.1 2422.73  4949.4 2434.41
  5100.8 2470.38  5191.6 2483.31  5373.3 2494.53  5454.1 2493.95  5504.5 2486.43
#Mann= 3 , 0 , 0
       0      .1       0  3867.1    .045       0  3882.1      .1       0
Bank Sta=3867.1,3882.1
XS Rating Curve= 0 ,0
Exp/Cntr=0.3,0.1

Type RM Length L Ch R = 1 ,82175.6 ,1842.1,1830.1,1807.3
XS GIS Cut Line= 4
     2048617.323      313900.728     2050247.926      312171.717
     2051607.312      312222.235     2052885.153      311581.686
#Sta/Elev= 30
       0 2441.43   402.8 2435.74   825.8 2437.52  1037.3 2431.32    1571 2424.87
  1651.6 2429.64  1903.3 2428.49  2024.2 2448.44  2054.4 2445.93  2104.7  2427.6
  2124.9 2426.21  2195.4 2425.08  2265.8 2428.95  2507.6 2423.28  2930.8 2421.67
  3381.6 2421.72  3396.6 2422.08  3505.2  2433.4    3616 2466.46  3696.6 2484.27
  3817.5 2497.93  3877.9 2499.27  4038.9 2488.72  4240.3 2442.11  4411.4 2430.78
    4653 2432.89  4723.4 2453.65  4844.2  2473.7  4914.7 2482.29  5166.4 2499.46
#Mann= 3 , 0 , 0
       0      .1       0  3381.6    .045       0  3396.6      .1       0
#XS Ineff= 2 , 0
         2035.43 2448.43
Permanent Ineff=
       F       F
Bank Sta=3381.6,3396.6
XS Rating Curve= 0 ,0
Exp/Cntr=0.3,0.1

Type RM Length L Ch R = 1 ,80345.5 ,1542.1,1559.7,1566.6
XS GIS Cut Line= 2
     2049202.799      313688.986     2052927.906      311792.504
#Sta/Elev= 30
       0 2471.64     212 2488.96   262.5 2488.88   292.8 2485.64   393.8 2459.35
   605.8 2426.62  1060.2 2418.18  1091.8 2418.59  1106.8  2419.4  1221.7 2424.44
  1292.4 2437.68  1332.8 2434.66  1383.3 2437.41  1433.8  2425.3  1474.1  2422.8
  1948.7 2421.34  2231.4 2457.58  2281.9 2470.26  2362.6 2478.12  2463.6 2479.48
  2584.8 2470.37  2615.1 2471.64  2796.8 2496.31  2907.9 2520.12  3008.8 2530.25
    3130 2515.76    3231  2495.1    3443 2435.29  3927.7 2437.91  4180.1 2448.97
#Mann= 3 , 0 , 0
       0      .1       0  1091.8    .045       0  1106.8      .1       0
#XS Ineff= 2 , 0
                         1297.61         2437.49
Permanent Ineff=
       F       F
Bank Sta=1091.8,1106.8
XS Rating Curve= 0 ,0
Exp/Cntr=0.3,0.1

Type RM Length L Ch R = 1 ,78785.8 ,1296.3,1299,1301.5
XS GIS Cut Line= 3
     2048764.869      314988.848     2049417.172      314656.755
      2052687.88      312991.612
#Sta/Elev= 30
       0 2461.81   140.4 2458.91   260.7 2442.03   842.9 2436.18  1125.2 2422.74
  1357.1 2423.76  1649.5 2416.06  1652.9  2416.1  1667.9 2416.62  1800.8 2422.83
  2335.2 2421.08  2365.4 2424.48  2385.6 2434.07  2395.6 2434.65  2446.1 2431.42
  2496.5 2433.87  2546.9 2421.78  3010.7 2418.55    3172 2424.12  3262.8 2430.51
  3393.9 2448.18  3484.6 2476.16  3555.2 2509.88  3605.6 2523.98  3696.4  2521.2
  3887.9 2471.72  3938.3  2462.7  4099.7  2463.4  4220.7 2475.22  4402.2 2463.92
#Mann= 3 , 0 , 0
       0     .08       0  1652.9    .045       0  1667.9      .1       0
#XS Ineff= 2 , 0
                         2404.78         2434.45
Permanent Ineff=
       F       F
Bank Sta=1652.9,1667.9
XS Rating Curve= 0 ,0
Exp/Cntr=0.3,0.1

Type RM Length L Ch R = 1 ,77486.7 ,1516,1520.5,1522.6
XS GIS Cut Line= 3
     2049172.086      316041.995     2050000.143      315620.425
     2053302.093      313939.376
#Sta/Elev= 30
       0 2466.48   149.9 2460.39   299.7 2442.02  1625.8 2416.04  1742.1 2416.07
  1757.1 2416.07  1908.5 2419.36  2655.6 2419.17  2675.8 2421.29  2706.1 2431.08
  2726.3 2432.22  2817.2 2423.42  2837.3 2425.04  2877.7 2418.86  3130.1 2421.22
  3291.7 2442.96  3352.2 2462.52  3382.5 2476.02  3402.7 2490.05  3443.1 2509.91
  3463.3 2515.51  3503.7 2518.08  3554.2 2513.78    3746 2450.78  3786.4 2442.31
  3836.8 2437.21  3988.3 2430.14  4533.5  2442.7    4594 2449.91  4634.4 2450.37
#Mann= 3 , 0 , 0
       0     .08       0  1742.1    .045       0  1757.1      .1       0
#XS Ineff= 2 , 0
                         2728.08         2432.05
Permanent Ineff=
       F       F
Bank Sta=1742.1,1757.1
XS Rating Curve= 0 ,0
Exp/Cntr=0.3,0.1

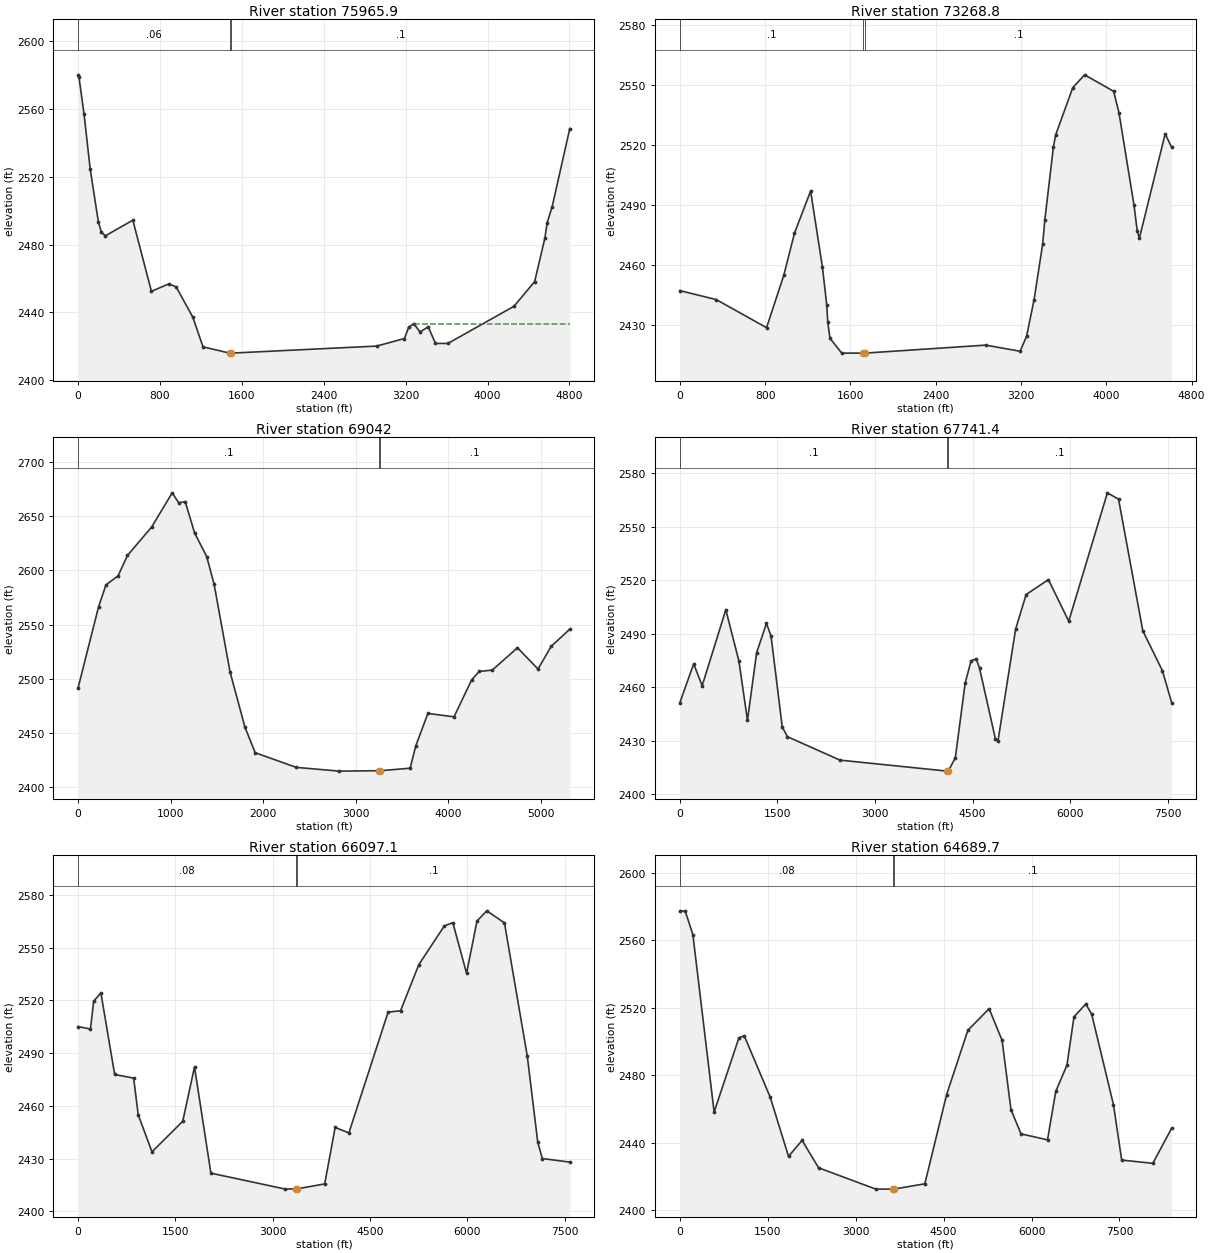
Type RM Length L Ch R = 1 ,75965.9 ,2691.4,2697.3,2697.8
XS GIS Cut Line= 3
     2049834.786      316918.333     2050358.037       316703.93
     2054278.957      315097.333
#Sta/Elev= 30
       0 2579.97     9.9 2578.44    59.5 2556.66     119 2524.47   198.4 2493.54
   228.2 2487.23   267.9 2485.18   535.7 2494.37   716.8 2452.48   888.3 2456.86
   958.9 2455.04  1120.4 2437.34  1221.2 2419.76  1479.8  2416.1  1483.6 2416.07
  1494.8 2416.07  2916.2 2420.22  3188.6 2424.67  3228.9 2431.24  3279.4 2433.48
  3339.9 2428.54  3420.6 2431.53  3491.2 2421.77  3612.3 2421.77    4258 2443.66
  4459.8 2458.19  4560.6 2484.01  4580.8  2492.6  4631.3 2502.41  4802.8 2548.34
#Mann= 3 , 0 , 0
       0     .06       0  1479.8    .045       0  1494.8      .1       0
#XS Ineff= 2 , 0
                         3281.67         2433.39
Permanent Ineff=
       F       F
Bank Sta=1479.8,1494.8
XS Rating Curve= 0 ,0
Exp/Cntr=0.3,0.1

Type RM Length L Ch R = 1 ,73268.8 ,4226.4,4226.2,4229.1
XS GIS Cut Line= 3
      2049941.14      317865.283     2050723.476      317843.785
     2054551.603      317738.593
#Sta/Elev= 30
       0 2447.25   341.2 2442.78   812.9 2428.76   974.1  2454.8  1074.9 2475.91
  1226.1 2496.97  1336.9 2459.02  1377.2 2440.24  1387.3 2431.39  1407.5 2423.51
  1518.3 2416.06  1721.6 2416.07  1736.6 2416.07  2868.7 2420.06  3191.2 2416.99
  3251.7 2424.47  3322.2 2442.77  3402.9 2470.64    3423 2482.67  3503.6    2519
  3523.8 2524.85    3685 2548.54  3795.9 2554.94    4068 2546.73  4118.4 2535.97
  4259.5 2489.83  4289.7 2476.91  4309.9 2473.44  4551.7  2525.5  4612.2 2518.72
#Mann= 3 , 0 , 0
       0      .1       0  1721.6    .045       0  1736.6      .1       0
Bank Sta=1721.6,1736.6
XS Rating Curve= 0 ,0
Exp/Cntr=0.3,0.1

Type RM Length L Ch R = 1 ,69042   ,1310.7,1301.7,1286.7
XS GIS Cut Line= 3
     2049418.061      319374.142     2051228.119      319667.897
     2054662.719      320225.299
#Sta/Elev= 30
       0 2491.47   221.7 2566.36   302.3 2586.72   433.2 2595.07     534 2613.83
     796  2640.1  1017.6 2671.59  1088.2 2662.42  1158.7 2663.45  1259.4 2634.69
  1390.4 2612.82    1471 2587.07  1642.3 2506.62  1803.5 2455.54  1914.4 2431.94
  2358.2 2418.43  2822.1 2414.97  3253.1 2415.37  3268.1 2415.38  3588.6 2417.68
  3649.2 2438.18  3780.3 2468.18  4062.7 2465.01  4254.3  2499.3    4335 2506.85
  4476.2 2508.15  4748.5 2528.72  4970.4 2509.09  5111.6 2529.97  5313.3 2545.83
#Mann= 3 , 0 , 0
       0      .1       0  3253.1    .045       0  3268.1      .1       0
Bank Sta=3253.1,3268.1
XS Rating Curve= 0 ,0
Exp/Cntr=0.3,0.1

Type RM Length L Ch R = 1 ,67741.4 ,1631,1643,1654.7
XS GIS Cut Line= 3
     2048501.227      321705.138     2051065.272       321201.62
     2055920.803      320248.107
#Sta/Elev= 30
       0 2451.32   211.9 2473.03     343 2460.81   706.2 2503.42     908  2474.6
  1039.2 2441.35  1180.4 2479.36  1331.7  2495.8  1402.4 2488.53  1573.9 2437.64
  1654.6 2432.19  2461.7 2419.05  4112.6 2412.88  4127.6 2412.93  4235.6  2420.4
  4386.7  2462.3  4477.4 2474.79  4558.1 2475.82  4608.4 2470.48  4850.3 2431.17
  4890.6 2429.66  5162.7 2492.57    5324 2511.95  5666.6 2520.32    5979 2496.99
  6573.6 2569.01    6745 2565.46  7117.9 2491.63  7420.2 2469.15  7561.3 2451.32
#Mann= 3 , 0 , 0
       0      .1       0  4112.6    .045       0  4127.6      .1       0
Bank Sta=4112.6,4127.6
XS Rating Curve= 0 ,0
Exp/Cntr=0.3,0.1

Type RM Length L Ch R = 1 ,66097.1 ,1414.6,1407.4,1400.2
XS GIS Cut Line= 4
     2049308.276      323160.644     2051802.369       322381.31
     2054928.419      321404.508     2056172.518      320258.977
#Sta/Elev= 30
       0 2505.18   191.7 2503.78   242.1 2519.69   353.1 2524.27     565 2477.91
   857.6 2475.84   928.2 2454.98    1140  2433.9  1614.2  2451.3  1795.8 2482.21
    2048 2421.79  3197.5  2412.7  3366.5 2412.91  3381.5  2412.9  3802.1 2415.67
  3963.4 2447.78    4175 2444.69  4779.6 2513.38  4971.1 2514.15  5253.3 2540.42
  5646.3 2562.45  5777.3 2564.24  5988.8 2535.44  6149.8 2565.24  6300.8    2571
  6572.6 2564.17    6925 2488.27    7086 2439.35  7156.5  2430.1  7579.3 2428.07
#Mann= 3 , 0 , 0
       0     .08       0  3366.5    .045       0  3381.5      .1       0
Bank Sta=3366.5,3381.5
XS Rating Curve= 0 ,0
Exp/Cntr=0.3,0.1

Type RM Length L Ch R = 1 ,64689.7 ,2077.6,2074.3,2057.8
XS GIS Cut Line= 6
     2049669.924      324488.843     2052435.767      323221.124
     2054100.624      322458.039     2055043.742      322025.762
     2055810.608      320658.692      2056684.16      320395.414
#Sta/Elev= 30
       0 2577.37    90.7 2577.24   221.6 2563.34   584.3  2458.2  1007.5 2502.17
  1098.1 2503.39  1541.4 2467.03  1853.7 2431.96  2085.4 2441.43  2367.5 2425.19
  3344.4 2412.57  3634.2 2412.59  3649.2 2412.58  4179.6 2415.72  4551.9 2468.56
  4914.2 2506.62  5276.8 2519.43  5498.4  2500.6  5649.5 2459.66  5820.8  2445.3
  6273.1 2441.76  6413.8  2470.4  6604.7 2485.97  6725.3 2514.64  6926.2 2522.21
  7026.7 2516.22  7398.5 2462.56    7539 2429.77  8070.4 2427.85  8391.2 2448.63
#Mann= 3 , 0 , 0
       0     .08       0  3634.2    .045       0  3649.2      .1       0
Bank Sta=3634.2,3649.2
XS Rating Curve= 0 ,0
Exp/Cntr=0.3,0.1

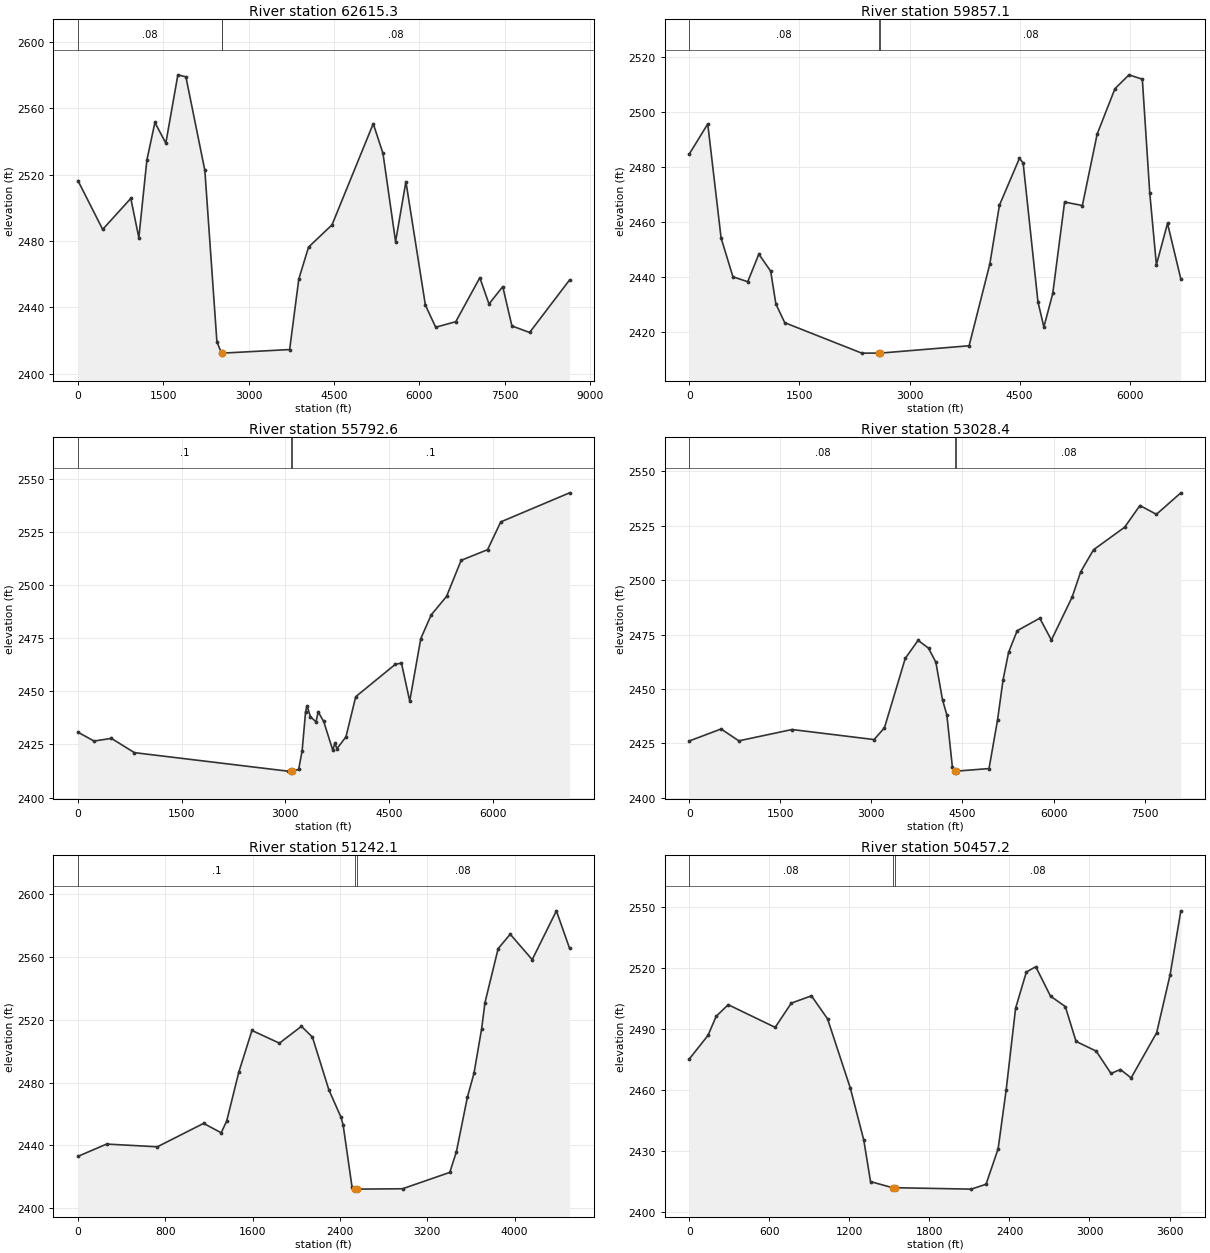
Type RM Length L Ch R = 1 ,62615.3 ,2646.3,2758.2,2763.7
XS GIS Cut Line= 5
     2050486.465      325395.524     2052799.692      324180.271
     2055294.452      322869.649     2055798.097      320804.918
     2056837.652      320497.743
#Sta/Elev= 30
       0 2516.46   433.8 2487.08   928.2 2505.79  1069.4 2482.11  1210.7 2528.89
  1351.9 2551.57  1543.6 2539.07  1755.5  2580.3  1896.7 2579.08  2229.6 2522.67
  2441.5 2419.33  2522.3 2412.47  2537.3 2412.47  3720.1 2414.63  3881.2 2457.18
  4052.2  2476.4  4464.9 2489.83  5189.5 2550.84  5360.6 2532.88  5582.2 2479.69
  5763.5 2515.89  6105.9 2441.41  6287.2  2428.1  6639.8 2431.42  7062.8 2457.95
    7224 2442.11  7465.7 2452.58  7626.6 2428.87  7937.8 2424.92  8640.4 2456.62
#Mann= 3 , 0 , 0
       0     .08       0  2522.3    .045       0  2537.3     .08       0
Bank Sta=2522.3,2537.3
XS Rating Curve= 0 ,0
Exp/Cntr=0.3,0.1

Type RM Length L Ch R = 1 ,59857.1 ,4171,4064.4,4051.5
XS GIS Cut Line= 2
     2051245.308      326727.643     2057162.932       323594.63
#Sta/Elev= 30
       0 2484.64   252.1 2495.56   433.6 2454.25     595 2440.14   796.6 2438.36
   947.9 2448.36  1109.2 2442.19  1179.8 2430.31  1300.8  2423.5  2349.6 2412.47
  2586.4 2412.48  2601.4 2412.48  3811.8 2415.14  4094.1 2444.79  4225.2 2466.12
  4497.5 2483.11  4547.9 2481.42  4749.6 2431.07  4830.3 2421.95  4951.3  2434.1
  5112.6 2467.25  5354.6 2465.99  5556.3 2491.91  5798.3 2508.34  5989.9 2513.37
  6171.4 2511.78  6272.3 2470.59    6363 2444.48  6514.3 2459.52  6695.8 2439.35
#Mann= 3 , 0 , 0
       0     .08       0  2586.4    .045       0  2601.4     .08       0
Bank Sta=2586.4,2601.4
XS Rating Curve= 0 ,0
Exp/Cntr=0.3,0.1

Type RM Length L Ch R = 1 ,55792.6 ,2788.9,2764.1,2737
XS GIS Cut Line= 4
      2051608.98      327952.856     2055328.142      326225.056
     2055591.705      325405.084     2057583.068      324585.111
#Sta/Elev= 30
       0 2430.78   231.8 2426.62   483.6 2427.88   816.2 2421.17  3032.9 2412.47
  3088.6 2412.49  3103.6 2412.49  3194.1 2413.29  3244.4 2422.08  3294.8 2440.49
    3315 2443.24  3365.4 2438.02    3446 2435.67  3476.2 2440.36  3556.8 2435.84
  3687.8 2422.32    3718 2425.63  3748.2 2423.01  3879.2 2428.63  4020.3  2447.5
  4591.6 2462.67  4681.8 2463.33    4802 2445.44  4962.2 2474.86  5113.2 2485.99
  5334.6 2494.66  5545.9 2511.64  5928.3 2516.64  6119.5 2529.72  7115.8  2543.4
#Mann= 3 , 0 , 0
       0      .1       0  3088.6    .045       0  3103.6      .1       0
Bank Sta=3088.6,3103.6
XS Rating Curve= 0 ,0
Exp/Cntr=0.3,0.1

Type RM Length L Ch R = 1 ,53028.4 ,1756.6,1786.3,1815.9
XS GIS Cut Line= 4
     2052077.536      328831.399     2055650.275      327835.718
     2055708.844      325580.792     2057700.207      324819.389
#Sta/Elev= 30
       0 2426.12   524.1 2431.63   816.4 2426.19  1693.2 2431.38  3043.7 2426.77
    3215 2432.16  3557.7 2464.05  3769.3 2472.33  3940.5 2468.75  4061.3 2462.31
  4172.1 2444.92  4242.6 2438.12  4333.2 2414.34  4373.5 2412.28  4384.8 2412.28
  4399.8 2412.28  4937.4 2413.46  5078.4  2435.9    5169 2454.24  5259.7 2466.83
  5400.6 2476.74  5773.2 2482.49  5964.6 2472.45  6306.5 2492.21  6447.3  2503.8
  6658.5 2513.91  7171.3 2524.27  7422.8 2534.23  7694.3 2530.18  8096.5 2540.05
#Mann= 3 , 0 , 0
       0     .08       0  4384.8    .045       0  4399.8     .08       0
Bank Sta=4384.8,4399.8
XS Rating Curve= 0 ,0
Exp/Cntr=0.3,0.1

Type RM Length L Ch R = 1 ,51242.1 ,790.9,784.9,778.9
XS GIS Cut Line= 3
     2053508.744      328822.271     2054510.258      328581.946
     2057888.666      327771.255
#Sta/Elev= 30
       0 2433.08   262.5 2440.88     727 2439.14  1150.8 2454.06  1311.9 2448.08
  1362.3 2455.51    1473 2486.59  1593.9 2513.27  1845.6 2505.18  2047.1  2515.9
  2147.8 2509.08  2298.8 2475.44  2409.6    2458  2429.7  2452.9  2510.3 2413.83
  2520.4 2412.17  2539.3 2412.17  2554.3 2412.17  2973.6 2412.41  3406.6 2422.83
    3467 2435.93  3567.7 2470.68  3628.1 2485.91  3698.6 2514.39  3728.8 2530.97
  3849.7 2565.42  3960.4  2574.6  4161.9  2558.4  4383.4  2589.5  4504.3 2565.59
#Mann= 3 , 0 , 0
       0      .1       0  2539.3    .045       0  2554.3     .08       0
Bank Sta=2539.3,2554.3
XS Rating Curve= 0 ,0
Exp/Cntr=0.3,0.1

Type RM Length L Ch R = 1 ,50457.2 ,2543.9,2543.2,2538
XS GIS Cut Line= 3
     2054902.003      329703.501     2055916.895      329147.307
     2058133.204      327932.698
#Sta/Elev= 30
       0 2475.37   140.9 2487.01   201.3  2496.3   291.8 2502.07   644.1 2490.92
   764.8 2502.83   915.8 2506.42  1036.5 2495.14  1207.6 2461.04  1308.3 2435.54
  1358.7 2415.18  1523.6 2412.17  1538.6 2412.17  2113.9 2411.47  2224.6 2413.87
  2315.2 2431.29  2375.6 2460.32  2446.1 2500.33  2526.7 2518.11  2597.2 2520.72
  2707.9 2506.26  2818.7 2501.15  2899.2 2484.03  3050.3 2479.26    3161 2468.29
  3231.5 2470.23  3312.1 2466.11  3503.4  2488.3  3604.1 2516.73  3684.6 2548.17
#Mann= 3 , 0 , 0
       0     .08       0  1523.6    .045       0  1538.6     .08       0
Bank Sta=1523.6,1538.6
XS Rating Curve= 0 ,0
Exp/Cntr=0.3,0.1

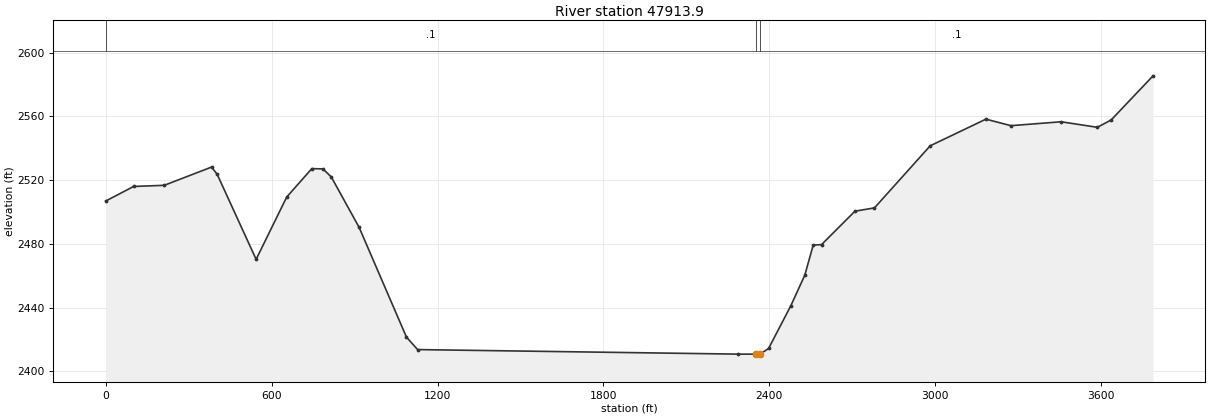
Type RM Length L Ch R = 1 ,47913.9 ,1161.5,1158.1,1154.6
XS GIS Cut Line= 3
     2055742.418      330918.909     2056546.145      330231.901
     2058621.913      328457.579
#Sta/Elev= 30
       0 2506.87   100.7    2516   211.5 2516.72   382.6 2528.16   402.8 2523.68
   543.8 2470.26   654.5 2509.38   745.2 2527.19   785.4 2527.03   815.7 2521.97
   916.4 2490.31  1087.6 2421.46  1127.9 2413.62  2286.7 2410.77  2351.8 2410.77
  2366.8 2410.77  2397.5 2414.34  2478.1 2441.22  2528.5 2460.35  2558.8 2479.18
    2589 2479.51  2709.9 2500.49  2780.4 2502.55    2982 2541.52  3183.5 2558.24
  3274.2 2554.15  3455.6 2556.61  3586.6 2553.12  3636.9 2557.78  3788.1 2585.44
#Mann= 3 , 0 , 0
       0      .1       0  2351.8    .045       0  2366.8      .1       0
Bank Sta=2351.8,2366.8
XS Rating Curve= 0 ,0
Exp/Cntr=0.3,0.1