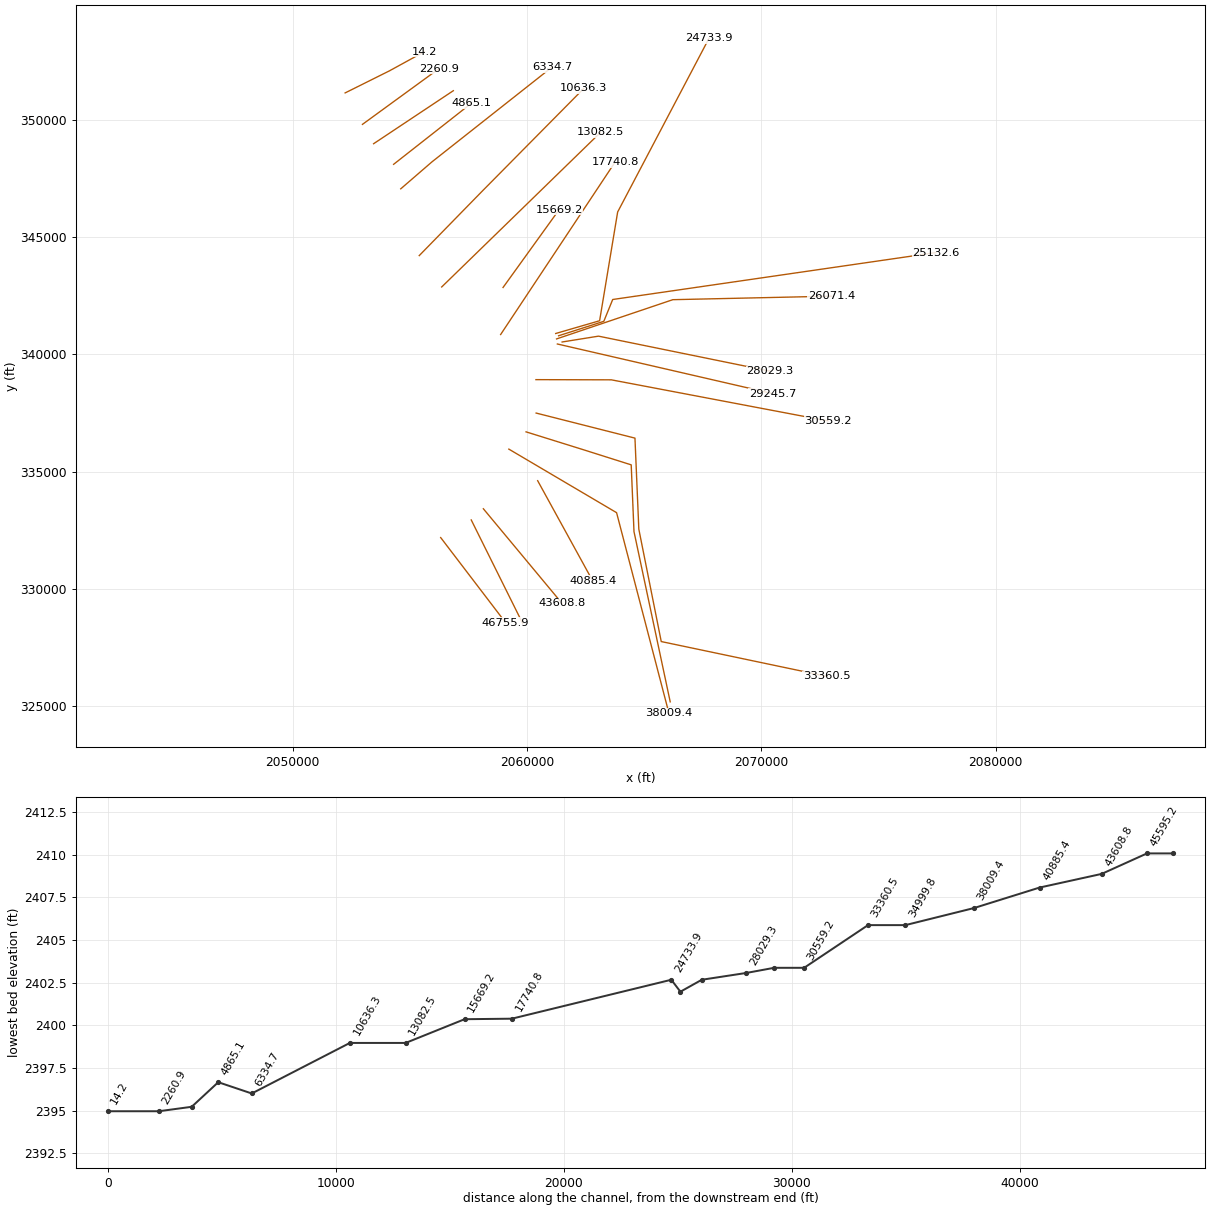
HEC-RAS study MeadowRv2.prj: MeadowRv2

--- MeadowRv2.g01 (geometry) --- (continued)

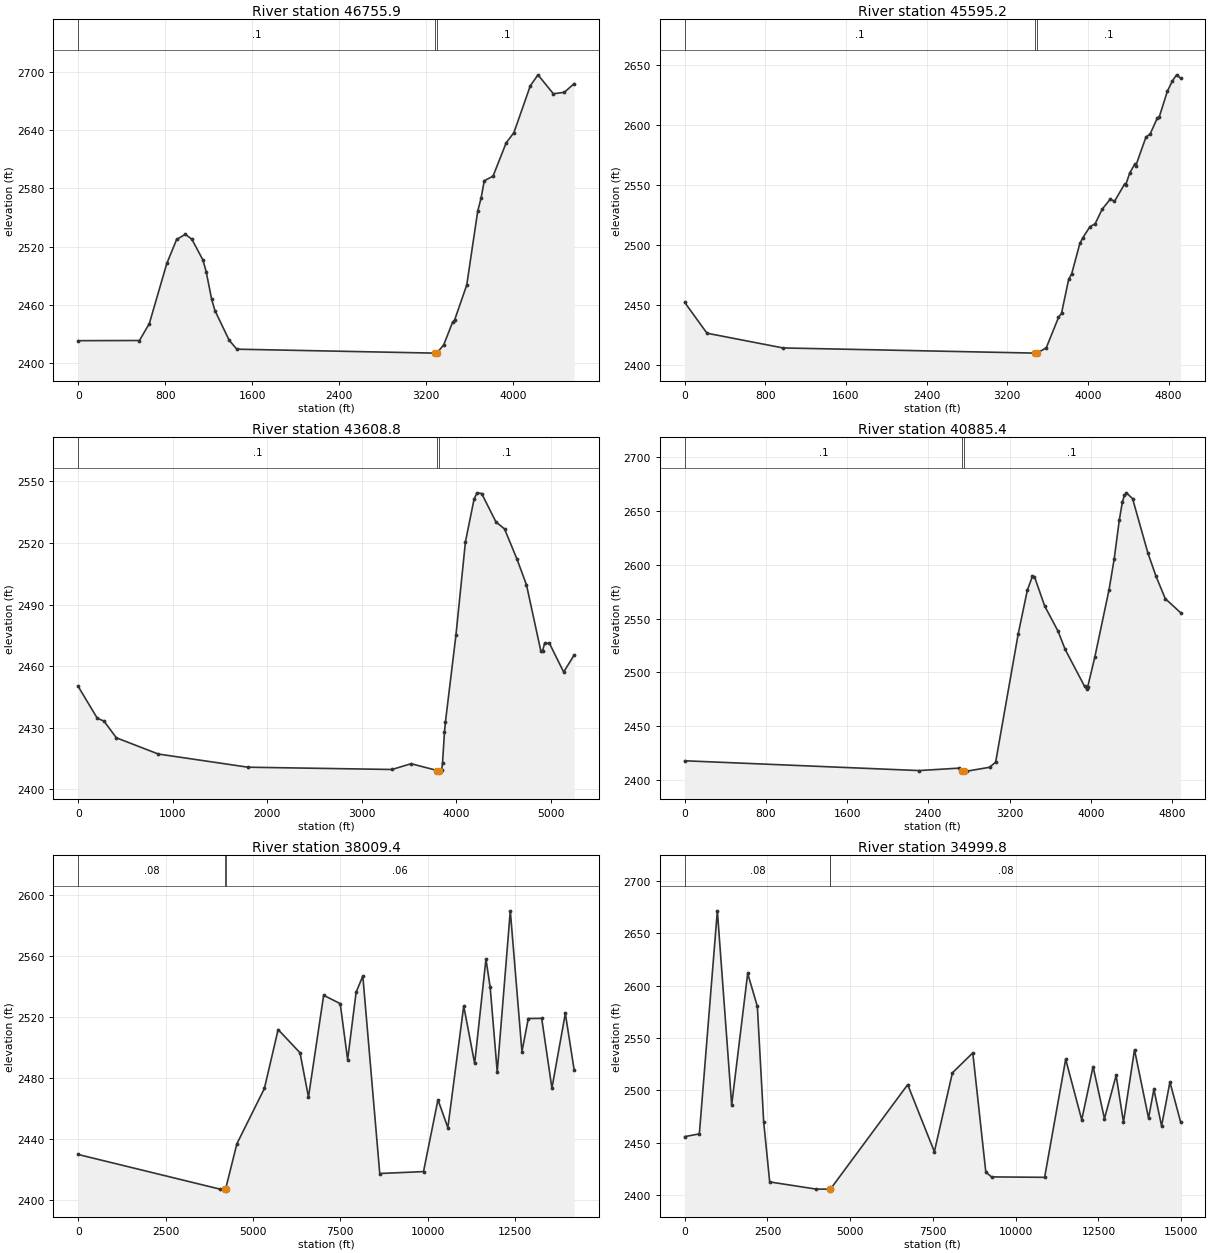
Type RM Length L Ch R = 1 ,46755.9 ,1167.1,1160.7,1153.9
XS GIS Cut Line= 3
     2056321.664      332186.458     2057706.539      330371.226
     2059088.227      328560.173
#Sta/Elev= 30
       0 2422.92   563.2  2423.1   653.8  2440.5   814.7 2502.56   905.2  2527.4
   985.7 2532.72    1046 2527.47  1146.6 2506.23  1176.8  2494.2  1227.1 2465.72
  1257.3 2454.03    1388 2423.46  1458.4 2414.14  3283.2 2410.07  3298.2  2410.1
  3361.7 2418.64  3442.3 2441.79  3462.5 2444.52  3573.3 2480.37  3674.1 2556.54
  3704.4  2569.7  3734.6 2587.96  3815.2 2592.71  3936.2 2627.15  4006.8 2637.56
    4158 2685.96  4228.5 2697.25  4369.6 2677.72  4470.4 2679.19  4561.1 2688.18
#Mann= 3 , 0 , 0
       0      .1       0  3283.2    .045       0  3298.2      .1       0
Bank Sta=3283.2,3298.2
XS Rating Curve= 0 ,0
Exp/Cntr=0.3,0.1

Type RM Length L Ch R = 1 ,45595.2 ,1982.2,1986.4,1989.8
XS GIS Cut Line= 3
     2057625.776      332938.311     2058543.448      331091.902
     2059815.116      328533.231
#Sta/Elev= 30
       0 2452.33   221.3 2426.66   975.6 2414.39  3479.2 2410.08  3494.2 2410.07
  3586.4 2414.48  3707.6 2439.78  3737.9 2443.34  3808.5 2471.49  3838.8 2476.24
  3919.6 2501.42  3949.9 2506.31  4020.6 2515.48    4071  2517.8  4141.7 2530.06
  4222.5 2538.46  4262.9 2536.48  4363.8 2550.98  4373.9 2550.08  4414.3 2560.16
  4464.8 2567.53  4474.9 2566.28  4575.9 2590.19  4616.2 2592.45  4686.9 2605.75
  4707.1 2606.85  4787.9 2628.29  4838.4 2636.98  4878.8 2641.92  4919.1  2639.1
#Mann= 3 , 0 , 0
       0      .1       0  3479.2    .045       0  3494.2      .1       0
Bank Sta=3479.2,3494.2
XS Rating Curve= 0 ,0
Exp/Cntr=0.3,0.1

Type RM Length L Ch R = 1 ,43608.8 ,2726.7,2723.2,2719.1
XS GIS Cut Line= 3
     2058142.586      333415.764     2059258.751      332072.968
     2061496.737      329380.571
#Sta/Elev= 30
       0 2450.09   201.9 2434.62   272.5 2433.24   403.7  2425.1   847.8 2417.19
  1796.6 2410.78  3320.1 2409.67  3521.9 2412.48  3800.3 2409.15  3815.3 2408.88
  3834.7 2408.87  3844.8 2409.27  3854.8 2413.03    3875  2427.8  3885.1 2432.74
  3996.1 2474.92    4097 2520.53  4187.8 2541.18  4218.1 2544.38  4268.5 2544.05
  4419.9 2530.19  4510.7 2526.81  4641.8 2512.16  4742.7  2499.6  4894.1 2467.49
  4914.2 2467.54  4934.4 2471.07  4984.9 2471.17  5136.2 2457.12  5247.2  2465.4
#Mann= 3 , 0 , 0
       0      .1       0  3800.3    .045       0  3815.3      .1       0
Bank Sta=3800.3,3815.3
XS Rating Curve= 0 ,0
Exp/Cntr=0.3,0.1

Type RM Length L Ch R = 1 ,40885.4 ,2867.3,2875.9,2891.6
XS GIS Cut Line= 3
     2060459.152      334613.383     2061279.412      333119.762
     2062810.581       330331.64
#Sta/Elev= 30
       0  2417.7    2308 2408.59  2700.6 2410.85  2733.5 2408.19  2748.5 2408.08
  2781.1 2408.07  3002.6 2411.64    3063 2416.42  3284.4 2535.29    3375 2576.28
  3425.3 2589.27  3445.5 2588.84  3546.1 2561.59    3677 2538.32  3747.5 2521.31
  3938.7 2486.95  3958.8 2484.58  3968.9 2486.17  4039.4 2513.93  4180.3 2576.96
  4230.6 2605.41    4281 2641.51  4311.2 2658.37  4331.3 2664.46  4351.4 2666.87
  4411.8 2661.45  4562.8 2610.86  4643.3  2589.1  4733.9  2568.4  4884.9 2555.43
#Mann= 3 , 0 , 0
       0      .1       0  2733.5    .045       0  2748.5      .1       0
Bank Sta=2733.5,2748.5
XS Rating Curve= 0 ,0
Exp/Cntr=0.3,0.1

Type RM Length L Ch R = 1 ,38009.4 ,3010.3,3009.5,3010.2
XS GIS Cut Line= 3
     2059230.147      335961.194     2063826.231      333249.132
     2066061.943      324683.066
#Sta/Elev= 30
       0 2429.63  4055.4 2406.87  4201.7  2406.9  4216.7 2406.91  4539.6 2436.66
  5326.5 2473.01  5720.2 2511.74  6346.1 2496.48  6588.3 2467.38  7022.4 2534.28
  7496.8 2528.76  7708.8 2491.92  7951.1 2536.23  8142.9 2546.96  8627.5 2417.14
  9879.2 2418.39 10293.1  2465.6 10575.7 2447.28   11030 2527.23 11342.9 2489.49
   11666 2558.07 11787.1  2539.5   11989 2483.91 12362.5 2589.78 12695.6 2497.19
 12877.3    2519 13260.9 2519.11 13553.6 2473.22 13937.2 2522.36 14189.6 2485.25
#Mann= 3 , 0 , 0
       0     .08       0  4201.7    .045       0  4216.7     .06       0
Bank Sta=4201.7,4216.7
XS Rating Curve= 0 ,0
Exp/Cntr=0.3,0.1

Type RM Length L Ch R = 1 ,34999.8 ,1623.4,1639.3,1646.8
XS GIS Cut Line= 5
     2059964.614      336697.892     2062396.983       335939.44
     2064450.471      335289.612      2064568.83      332441.301
     2066114.389      325175.166
#Sta/Elev= 30
       0 2455.93   443.1 2458.57   986.9 2671.28    1420 2486.08  1903.4 2611.59
  2195.4 2580.11  2386.7 2469.92    2568 2412.74  3977.1 2405.87  4388.3  2405.9
  4403.3  2405.9  6736.6 2505.52  7542.4 2441.55  8087.4  2516.8  8703.1 2535.82
  9096.8 2422.13  9268.4 2417.53 10873.2 2417.14 11509.1 2529.67 11993.6 2472.02
 12336.7 2522.77 12679.9 2473.08 13033.2 2514.33 13255.2 2469.69 13588.3 2538.77
 14012.2 2473.64 14173.7 2501.07 14405.9 2466.07 14658.2 2508.01 14981.2 2469.94
#Mann= 3 , 0 , 0
       0     .08       0  4388.3    .045       0  4403.3     .08       0
Bank Sta=4388.3,4403.3
XS Rating Curve= 0 ,0
Exp/Cntr=0.3,0.1

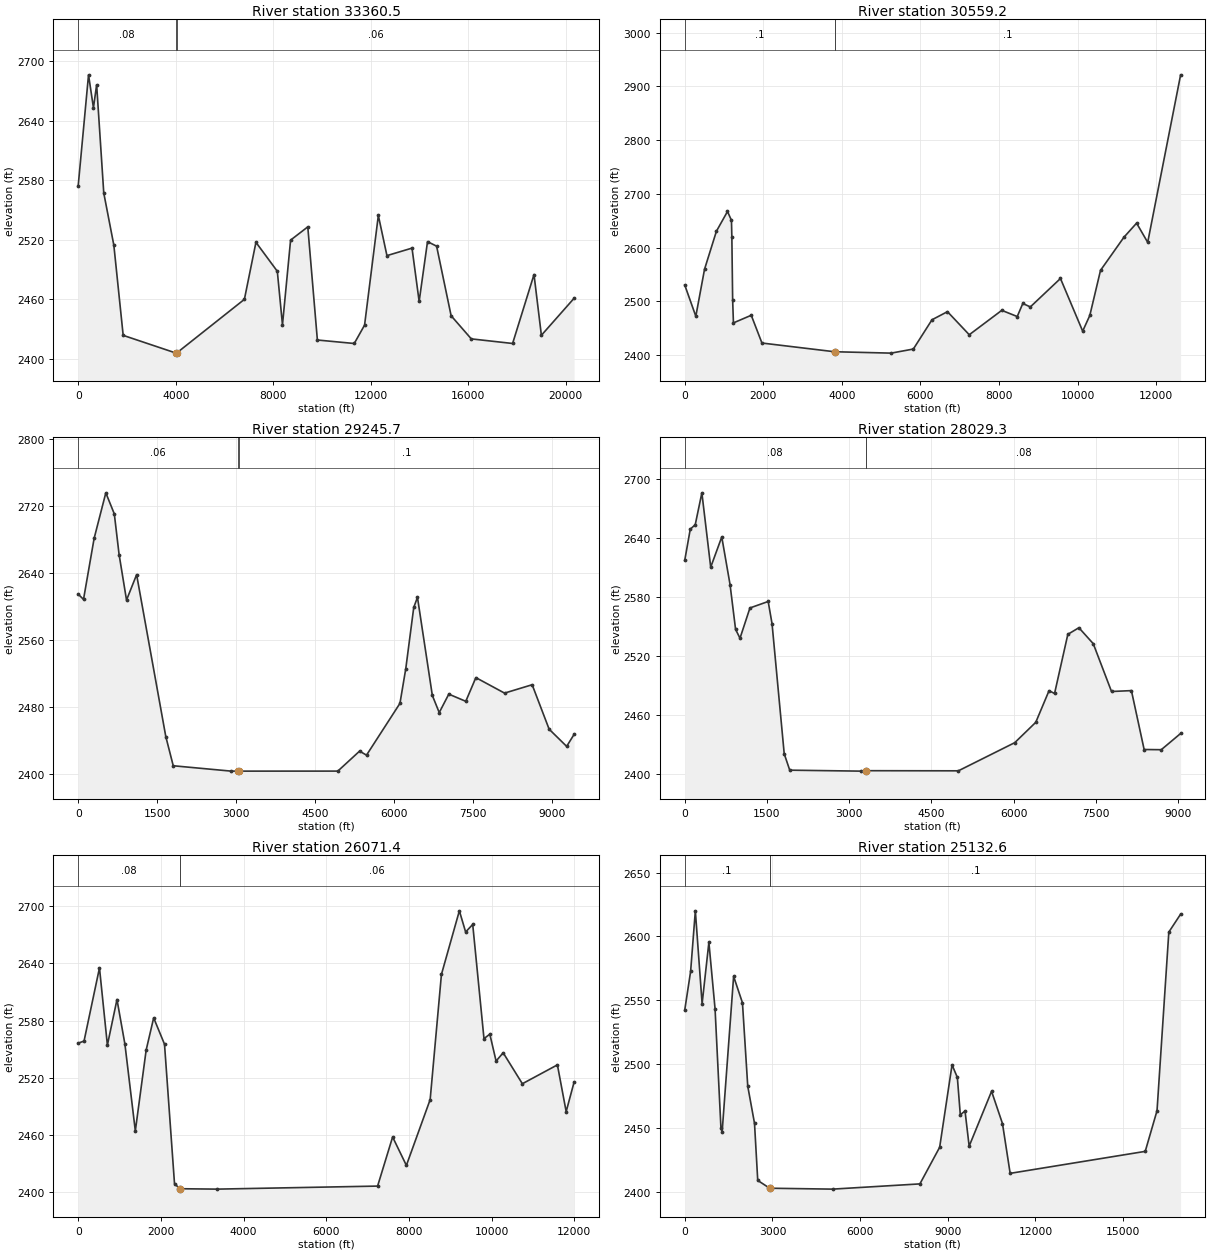
Type RM Length L Ch R = 1 ,33360.5 ,2793.2,2801.2,2801.9
XS GIS Cut Line= 6
     2060394.342      337499.969     2062847.061      336877.875
     2064610.575      336430.586     2064775.442      332544.607
     2065731.933      327748.292        2072792.      326263.593
#Sta/Elev= 30
       0 2574.47   423.4 2686.01     625 2652.82   756.1 2676.03  1048.4 2567.04
  1461.8 2514.54  1844.9 2423.76  4018.9 2405.87  4033.9 2405.87  6818.4 2460.02
    7292 2517.41  8168.7 2488.26  8380.4 2434.39  8713.2 2519.62    9419 2532.96
  9812.3 2419.07 11324.9 2415.57 11748.5 2434.05 12313.2 2544.44 12666.1 2504.02
   13695 2511.58 13987.6 2457.91 14330.7 2518.11   14704 2513.53 15299.4  2443.5
 16126.8 2420.21 17821.9 2415.58 18699.8 2484.97 19002.5 2423.83 20344.5 2461.09
#Mann= 3 , 0 , 0
       0     .08       0  4018.9    .045       0  4033.9     .06       0
Bank Sta=4018.9,4033.9
XS Rating Curve= 0 ,0
Exp/Cntr=0.3,0.1

Type RM Length L Ch R = 1 ,30559.2 ,1321.8,1313.6,1298.3
XS GIS Cut Line= 3
     2060385.703      338926.383      2063601.14      338918.455
     2072845.166      337163.649
#Sta/Elev= 30
       0  2530.2   282.2 2472.04     504 2559.55   806.4 2630.29  1088.6 2667.15
  1189.4 2650.53  1199.5 2619.56  1219.6  2502.8  1239.8 2459.67  1693.4 2473.86
  1965.6 2422.16  3816.7 2405.91  3831.7 2405.92  5254.8 2403.37  5820.1 2410.98
  6294.6 2465.46  6688.3 2480.56  7243.6  2437.6  8071.4 2483.02  8465.2  2471.5
  8606.5  2495.8  8798.3 2489.39  9565.6 2542.33 10130.9 2444.31 10312.7  2473.5
 10585.2 2557.46 11180.9  2619.1 11503.9  2645.4 11786.6 2609.58 12624.6 2921.52
#Mann= 3 , 0 , 0
       0      .1       0  3816.7    .045       0  3831.7      .1       0
Bank Sta=3816.7,3831.7
XS Rating Curve= 0 ,0
Exp/Cntr=0.3,0.1

Type RM Length L Ch R = 1 ,29245.7 ,1213.5,1216.4,1218.7
XS GIS Cut Line= 2
     2061300.076      340447.815     2070482.944      338330.318
#Sta/Elev= 30
       0 2614.67   100.9 2608.42   302.7 2681.32   524.7 2735.66   686.1 2710.48
   776.9 2662.02   918.2 2607.62  1109.9 2637.95  1664.8 2444.53  1806.1 2409.78
  2905.8 2403.37  3039.9 2403.37  3054.9 2403.37  4933.9  2403.4  5347.6 2427.27
  5478.7 2422.43  6114.4 2484.28  6225.4 2525.83  6376.7 2598.82  6447.4 2610.86
  6729.9 2493.72    6861 2473.27  7042.7  2495.3  7365.5 2486.73  7557.2 2515.02
  8102.1 2496.52  8626.8 2506.53  8949.6 2453.42  9282.6 2432.92  9423.8 2447.25
#Mann= 3 , 0 , 0
       0     .06       0  3039.9    .045       0  3054.9      .1       0
Bank Sta=3039.9,3054.9
XS Rating Curve= 0 ,0
Exp/Cntr=0.3,0.1

Type RM Length L Ch R = 1 ,28029.3 ,1945.5,1957.9,1962.2
XS GIS Cut Line= 3
     2061502.932      340533.429     2063055.332      340782.579
     2070376.527      339287.676
#Sta/Elev= 30
       0 2617.23   100.8 2648.91   191.5 2653.45   312.4 2685.85   473.7 2610.28
   675.3 2641.02   826.4 2592.67   927.2 2547.14  1007.9  2538.1  1189.3 2568.87
  1521.9 2575.44  1592.4 2552.87  1814.3 2420.72  1915.1 2404.04  3205.9 2403.07
  3298.7 2403.35  3313.7 2403.51  4990.8 2403.38  6019.3    2432  6402.5 2452.67
  6644.5  2484.8  6745.4 2481.96  6987.4 2542.06  7189.1 2548.78  7451.2 2532.55
    7784 2483.98    8147 2484.88    8379 2425.04  8691.6 2424.83  9044.5 2441.32
#Mann= 3 , 0 , 0
       0     .08       0  3298.7    .045       0  3313.7     .08       0
Bank Sta=3298.7,3313.7
XS Rating Curve= 0 ,0
Exp/Cntr=0.3,0.1

Type RM Length L Ch R = 1 ,26071.4 ,919.3,938.8,957.1
XS GIS Cut Line= 3
     2061266.062      340664.267     2066225.392      342339.057
     2072985.861      342489.324
#Sta/Elev= 30
       0  2556.2   141.2 2558.41   514.4 2635.35     706 2554.14     938 2602.11
  1129.6 2555.27  1381.7 2463.89    1644 2548.95  1825.5 2582.78  2087.7 2555.09
  2329.8 2408.39  2457.6 2403.11  2472.6 2403.09  3358.5 2402.67  7242.9 2405.87
  7606.3 2457.51  7939.3 2427.62  8514.6 2496.84  8787.1 2628.45  9221.1 2695.38
  9372.5 2673.13  9544.1 2681.05  9816.6 2560.94  9957.9 2565.68 10109.3 2537.37
 10280.9 2546.07 10745.1 2513.51 11592.9 2533.36 11804.9  2484.2 11996.6 2515.26
#Mann= 3 , 0 , 0
       0     .08       0  2457.6    .045       0  2472.6     .06       0
Bank Sta=2457.6,2472.6
XS Rating Curve= 0 ,0
Exp/Cntr=0.3,0.1

Type RM Length L Ch R = 1 ,25132.6 ,391.6,398.6,405.7
XS GIS Cut Line= 4
     2061353.095      340799.093     2063281.947      341415.531
     2063661.102       342346.92     2077452.028      344349.872
#Sta/Elev= 30
       0 2542.21   201.5 2572.57   362.7 2619.99   594.4 2547.22   826.1  2595.3
  1037.7 2543.15  1239.2 2449.61  1279.4 2446.74  1672.4 2568.62  1974.6 2547.96
  2155.7 2482.61    2387 2453.55  2497.6 2408.79  2906.4 2402.67  2921.4 2402.67
  5058.8 2401.97  8045.8 2406.07  8721.9 2434.75  9145.7 2499.31  9327.3 2489.46
  9428.2  2460.2  9589.7 2463.17    9731 2435.62 10497.9  2478.6 10871.2 2453.32
 11133.6 2414.33 15755.3 2431.55 16158.9  2463.4 16562.6 2603.33 16966.2 2617.39
#Mann= 3 , 0 , 0
       0      .1       0  2906.4    .045       0  2921.4      .1       0
Bank Sta=2906.4,2921.4
XS Rating Curve= 0 ,0
Exp/Cntr=0.3,0.1

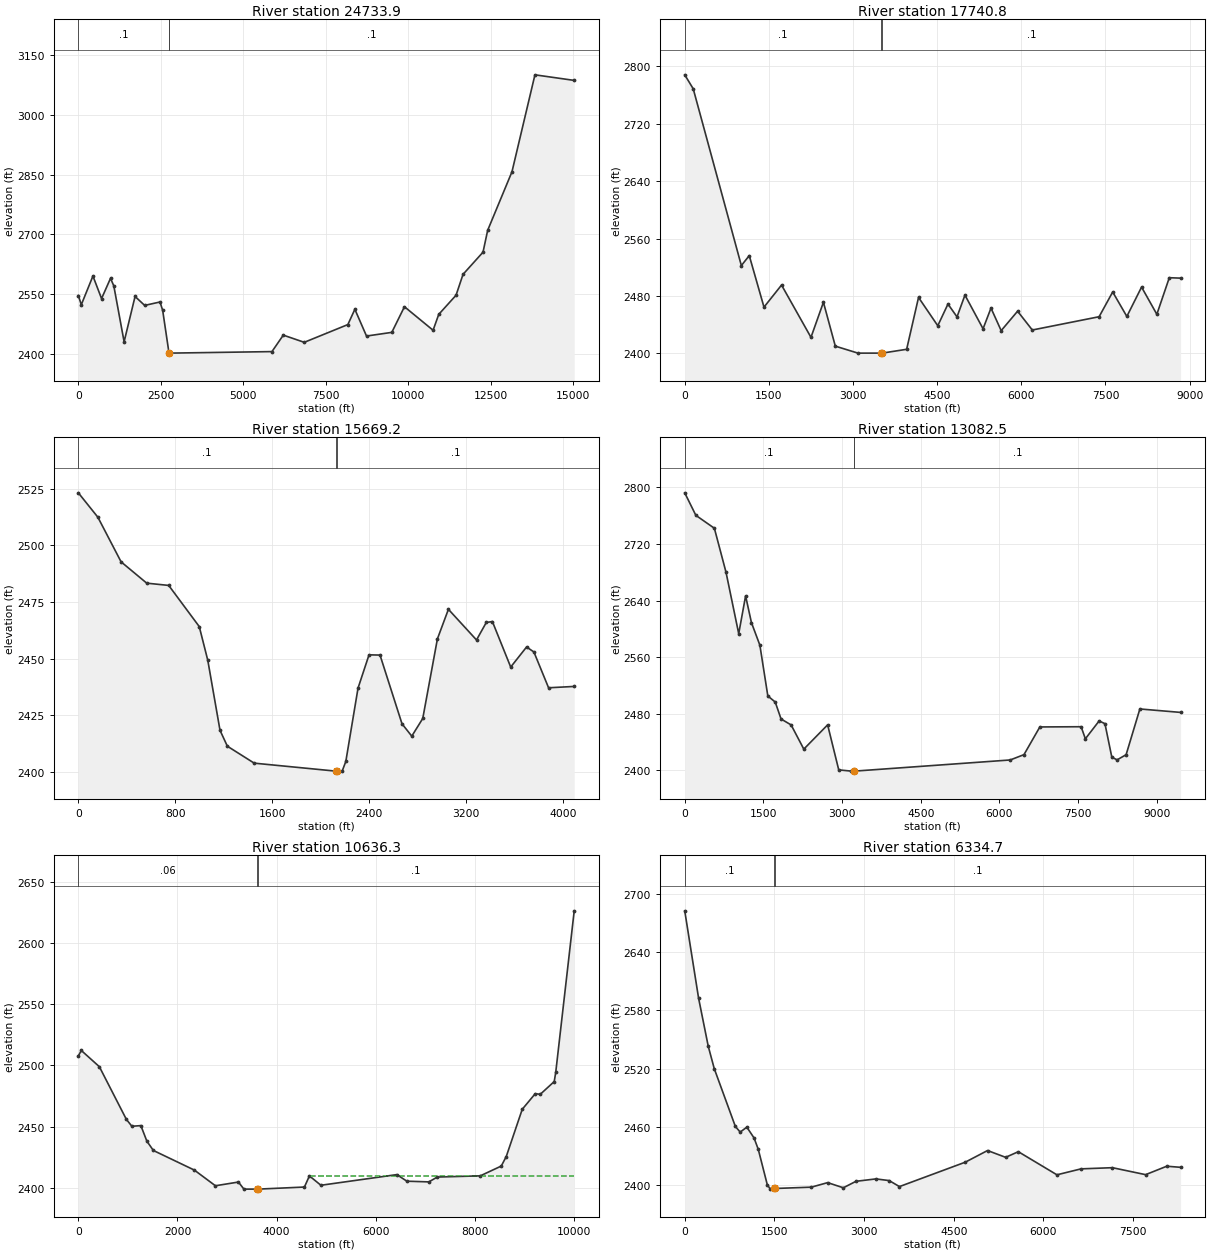
Type RM Length L Ch R = 1 ,24733.9 ,6970.7,6993.1,6960.9
XS GIS Cut Line= 4
     2061229.674       340895.83     2063102.478       341440.25
     2063872.336      346082.041     2067768.923      353493.027
#Sta/Elev= 30
       0 2546.88    90.5 2523.95   442.3  2595.8   703.7 2539.26   975.2 2590.01
  1075.7 2570.96  1387.4  2431.1  1719.1 2544.57  2010.9 2522.18  2475.4 2530.77
  2556.2 2509.77  2747.8 2402.87  2762.8 2402.67    5868  2406.5  6211.3 2447.75
  6847.2 2429.74  8168.7  2474.2  8380.6  2512.5  8733.6 2445.44  9500.3 2454.66
  9883.6 2518.87 10751.2 2459.94 10922.7 2499.72 11447.3 2547.69 11659.1 2599.99
 12264.4 2655.52 12405.6  2710.3   13142 2856.84 13838.1 3099.68 15028.5 3085.72
#Mann= 3 , 0 , 0
       0      .1       0  2747.8    .045       0  2762.8      .1       0
Bank Sta=2747.8,2762.8
XS Rating Curve= 0 ,0
Exp/Cntr=0.3,0.1

Type RM Length L Ch R = 1 ,17740.8 ,2067.6,2071.6,2065
XS GIS Cut Line= 2
     2058879.604      340851.715     2063766.375      348217.534
#Sta/Elev= 30
       0 2788.07   151.4 2768.58  1009.1 2522.35  1150.3 2536.23  1412.7 2464.47
  1725.5 2495.22  2250.2 2422.37  2472.2 2471.24  2684.1 2410.12  3087.8 2400.39
  3505.4 2400.41  3520.4 2400.41  3955.6 2405.73  4167.5 2477.98  4510.5 2438.55
  4692.2 2468.75  4853.6 2450.87  4994.9 2481.22  5317.8 2434.33  5459.1 2463.14
  5640.7 2431.71  5933.3 2458.79  6195.7 2432.59  7386.4  2451.1  7628.6 2485.57
  7880.8  2451.5  8143.2 2492.39  8415.6 2454.48  8637.6 2505.45  8839.4 2504.85
#Mann= 3 , 0 , 0
       0      .1       0  3505.4    .045       0  3520.4      .1       0
Bank Sta=3505.4,3520.4
XS Rating Curve= 0 ,0
Exp/Cntr=0.3,0.1

Type RM Length L Ch R = 1 ,15669.2 ,2593.2,2586.7,2578.1
XS GIS Cut Line= 2
     2058982.925      342859.795     2061374.304      346179.233
#Sta/Elev= 30
       0 2523.23   161.2 2512.46   352.7 2492.76   564.3 2483.35   745.7 2482.35
   997.6 2464.18  1068.1 2449.27  1168.9 2418.37  1229.4 2411.37    1451 2403.88
  2122.1 2400.37  2137.1 2400.37  2176.6 2400.36  2206.8 2404.64  2307.6 2437.02
  2398.2  2451.7  2488.9  2451.6  2670.3 2421.26  2750.9  2415.8  2841.6 2423.61
  2962.5 2458.76  3053.2  2471.8    3285 2458.27  3365.6 2465.99    3416  2466.4
  3567.1 2446.31  3698.1 2455.17  3758.6 2452.96  3879.5 2437.16  4091.1 2437.75
#Mann= 3 , 0 , 0
       0      .1       0  2122.1    .045       0  2137.1      .1       0
Bank Sta=2122.1,2137.1
XS Rating Curve= 0 ,0
Exp/Cntr=0.3,0.1

Type RM Length L Ch R = 1 ,13082.5 ,2437.5,2446.2,2431.9
XS GIS Cut Line= 2
     2056364.997      342881.734     2063140.009      349476.361
#Sta/Elev= 30
       0 2792.22   211.9 2760.42   565.1 2742.13     787 2679.99  1029.2 2593.16
  1160.4 2646.59  1271.4 2608.91  1432.8 2576.87  1584.2 2505.17  1725.4 2496.58
  1836.4 2472.64  2028.2 2464.27  2270.3 2430.06  2724.4 2464.35  2936.3 2400.72
  3178.4 2398.97  3220.3 2398.97  3235.3 2398.97  6205.5 2414.74  6467.9 2422.26
  6770.6  2461.4  7557.6 2461.71  7638.4 2444.64  7900.7 2469.88  8011.7 2466.02
  8142.9 2418.62  8243.8 2414.92  8415.3 2422.18  8677.7 2486.81  9454.6 2481.95
#Mann= 3 , 0 , 0
       0      .1       0  3220.3    .045       0  3235.3      .1       0
Bank Sta=3220.3,3235.3
XS Rating Curve= 0 ,0
Exp/Cntr=0.3,0.1

Type RM Length L Ch R = 1 ,10636.3 ,4298.8,4301.6,4301.1
XS GIS Cut Line= 3
     2055407.081      344220.809     2058123.243      347000.898
     2062425.938      351352.608
#Sta/Elev= 30
       0  2507.7    60.6 2512.13     424 2498.91   969.2 2455.92  1080.2 2450.29
  1261.9 2450.81  1383.1  2438.1  1514.3 2430.52  2342.1 2414.49  2766.1 2401.72
  3230.5 2404.75  3341.6 2398.97  3614.9 2398.98  3629.9 2398.98  4562.2 2400.67
    4663 2409.77  4894.9 2402.12  6427.3 2410.82    6629 2405.45  7072.6 2404.88
    7244 2408.83    8111 2409.81  8534.4 2417.81  8635.2 2425.59  8957.9 2464.16
    9220 2476.89  9320.8 2476.36  9603.1 2486.78  9633.4 2494.27 10006.4 2626.14
#Mann= 3 , 0 , 0
       0     .06       0  3614.9    .045       0  3629.9      .1       0
#XS Ineff= 2 , 0
                         4667.85         2410.03
Permanent Ineff=
       F       F
Bank Sta=3614.9,3629.9
XS Rating Curve= 0 ,0
Exp/Cntr=0.3,0.1

Type RM Length L Ch R = 1 ,6334.7  ,1470,1469.6,1469.1
XS GIS Cut Line= 3
     2054618.015      347070.176     2055953.662      348224.222
     2061080.495      352271.132
#Sta/Elev= 30
       0 2682.36     232 2592.39   393.4    2543   494.2 2519.92   847.3 2460.45
     928  2454.7  1038.9 2459.78    1160 2448.61  1230.6 2436.89  1381.9 2400.38
  1432.3 2396.01  1492.6 2396.67  1507.6 2396.67  2118.5 2398.04  2391.1  2402.7
  2653.5  2397.4  2865.5 2404.06  3198.7 2406.52  3420.8  2404.8  3592.4 2398.62
  4692.8 2423.71  5066.3 2435.72  5369.2 2428.73  5581.2 2434.53  6227.2 2410.74
    6631 2416.86    7156 2418.07  7711.2  2410.9  8064.6 2419.57  8296.8 2418.45
#Mann= 3 , 0 , 0
       0      .1       0  1492.6    .045       0  1507.6      .1       0
Bank Sta=1492.6,1507.6
XS Rating Curve= 0 ,0
Exp/Cntr=0.3,0.1

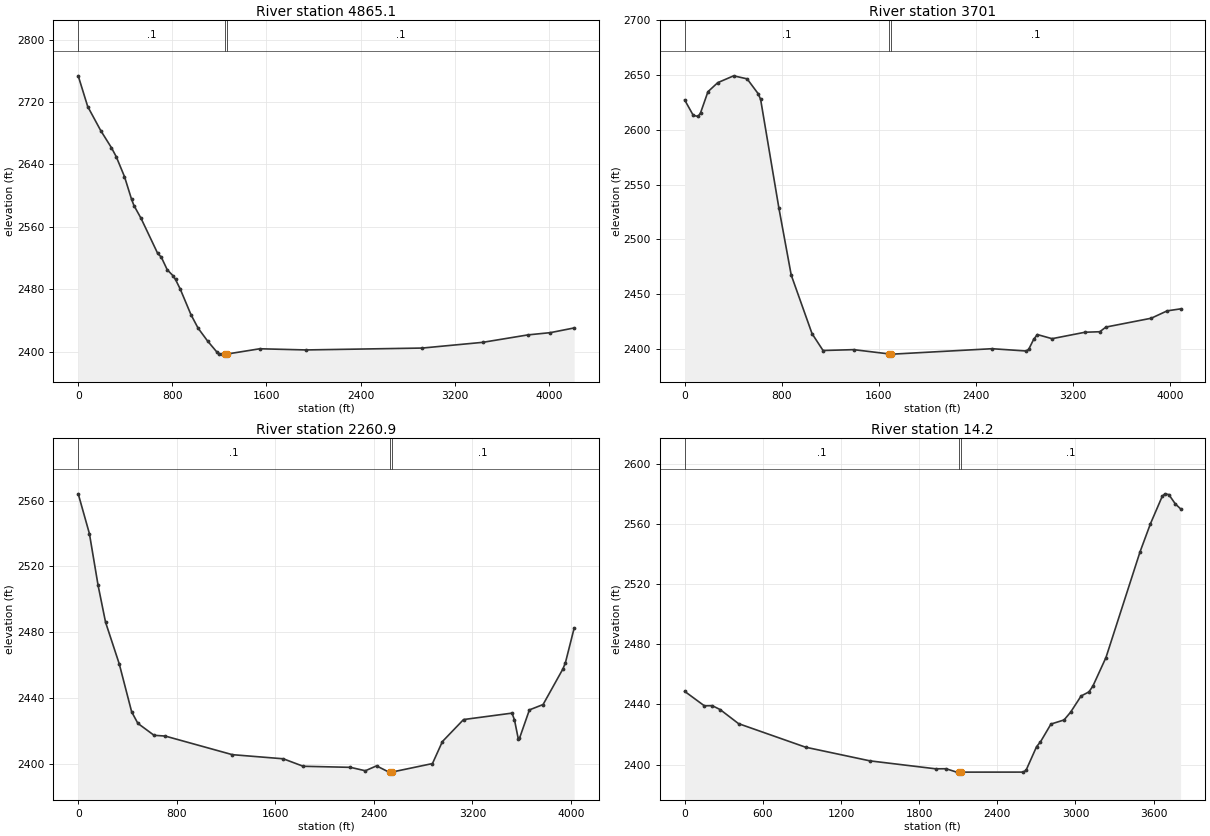
Type RM Length L Ch R = 1 ,4865.1  ,1165.7,1164.1,1162.4
XS GIS Cut Line= 2
     2054313.668       348116.06     2057629.491      350720.333
#Sta/Elev= 30
       0 2753.56    80.7 2714.17   191.6 2683.31   282.4 2661.39   322.8 2650.03
   393.4 2624.32   453.9 2595.07   474.1 2587.16   534.6 2570.69   675.8 2525.78
   706.1 2521.12   756.5 2504.94   806.9 2497.04   827.1 2492.39   867.5 2480.07
   958.2 2447.42  1018.8 2430.07  1099.5 2413.57  1180.2 2399.12  1200.3 2396.79
  1220.5 2396.67  1245.9 2396.67  1260.9 2396.68  1543.3 2403.54  1936.7 2402.04
  2925.2 2404.46  3439.6  2411.8  3822.9 2421.33  4014.5 2424.24  4216.3 2430.26
#Mann= 3 , 0 , 0
       0      .1       0  1245.9    .045       0  1260.9      .1       0
Bank Sta=1245.9,1260.9
XS Rating Curve= 0 ,0
Exp/Cntr=0.3,0.1

Type RM Length L Ch R = 1 ,3701    ,1436.3,1440.2,1444.1
XS GIS Cut Line= 2
     2053460.241      348995.383     2056861.119      351258.251
#Sta/Elev= 30
       0 2627.39    70.6 2613.35     111 2612.34   131.1 2615.73   191.6 2634.92
   272.3  2643.2   403.4 2649.44   514.4 2646.67   605.2 2633.13   625.4 2627.96
   776.6 2528.26   877.5 2467.47    1049 2413.96  1139.7 2398.54  1391.9 2399.32
  1682.9 2395.43  1697.9 2395.32  1714.7 2395.23  2531.6 2400.18    2814 2398.08
  2834.2 2399.74  2874.6 2408.75  2904.8 2413.11  3025.9 2409.34  3298.2 2415.24
  3419.2 2415.68  3469.7 2419.95  3842.8 2428.02    3974 2434.75  4084.9 2436.58
#Mann= 3 , 0 , 0
       0      .1       0  1682.9    .045       0  1697.9      .1       0
Bank Sta=1682.9,1697.9
XS Rating Curve= 0 ,0
Exp/Cntr=0.3,0.1

Type RM Length L Ch R = 1 ,2260.9  ,2249.1,2246.7,2243.7
XS GIS Cut Line= 2
     2052984.106      349821.175     2056238.128      352191.366
#Sta/Elev= 30
       0 2564.06    90.8 2539.91   161.4 2508.42     222 2486.04     333 2460.76
   433.8  2431.6   484.3 2424.59   615.5 2417.35   706.3 2416.88  1251.1 2405.58
  1664.8 2403.07  1826.2 2398.53  2209.6 2397.88  2330.7  2395.8  2421.5 2398.77
  2522.4 2394.97  2529.4 2394.97  2544.4 2394.97  2875.5 2400.17  2956.2 2413.54
  3127.8 2426.91  3521.2 2430.82  3541.4 2426.71  3571.7 2415.35  3581.8 2415.47
  3662.5 2432.78  3773.5 2436.04  3934.9 2457.74  3955.1 2461.55  4025.7 2482.47
#Mann= 3 , 0 , 0
       0      .1       0  2529.4    .045       0  2544.4      .1       0
Bank Sta=2529.4,2544.4
XS Rating Curve= 0 ,0
Exp/Cntr=0.3,0.1

Type RM Length L Ch R = 1 ,14.2    ,32.8,14.2,0
XS GIS Cut Line= 3
     2052245.189      351163.352     2054140.976      352108.205
     2055622.238      352920.421
#Sta/Elev= 30
       0 2448.67   151.3 2439.04   211.8 2439.15   272.3 2436.56   413.6  2427.2
     928 2411.55  1422.2 2402.46  1926.6 2397.18  2007.2 2397.22  2087.9 2394.97
  2107.3 2394.97  2122.3 2394.97  2600.9 2394.99    2621 2396.22  2701.4 2411.86
  2731.6  2415.1    2812 2426.92  2912.6 2429.66  2962.9 2434.82  3043.3 2445.57
  3103.6 2448.31  3133.8 2452.14  3234.4 2471.17  3495.8 2541.38  3576.2 2560.18
  3666.8  2578.4  3686.9 2579.98    3717 2579.47  3767.3 2573.24  3807.5 2569.98
#Mann= 3 , 0 , 0
       0      .1       0  2107.3    .045       0  2122.3      .1       0
Bank Sta=2107.3,2122.3
XS Rating Curve= 0 ,0
Exp/Cntr=0.3,0.1

Chan Stop Cuts=-1
Use User Specified Reach Order=0
Composite Channel Slope=5